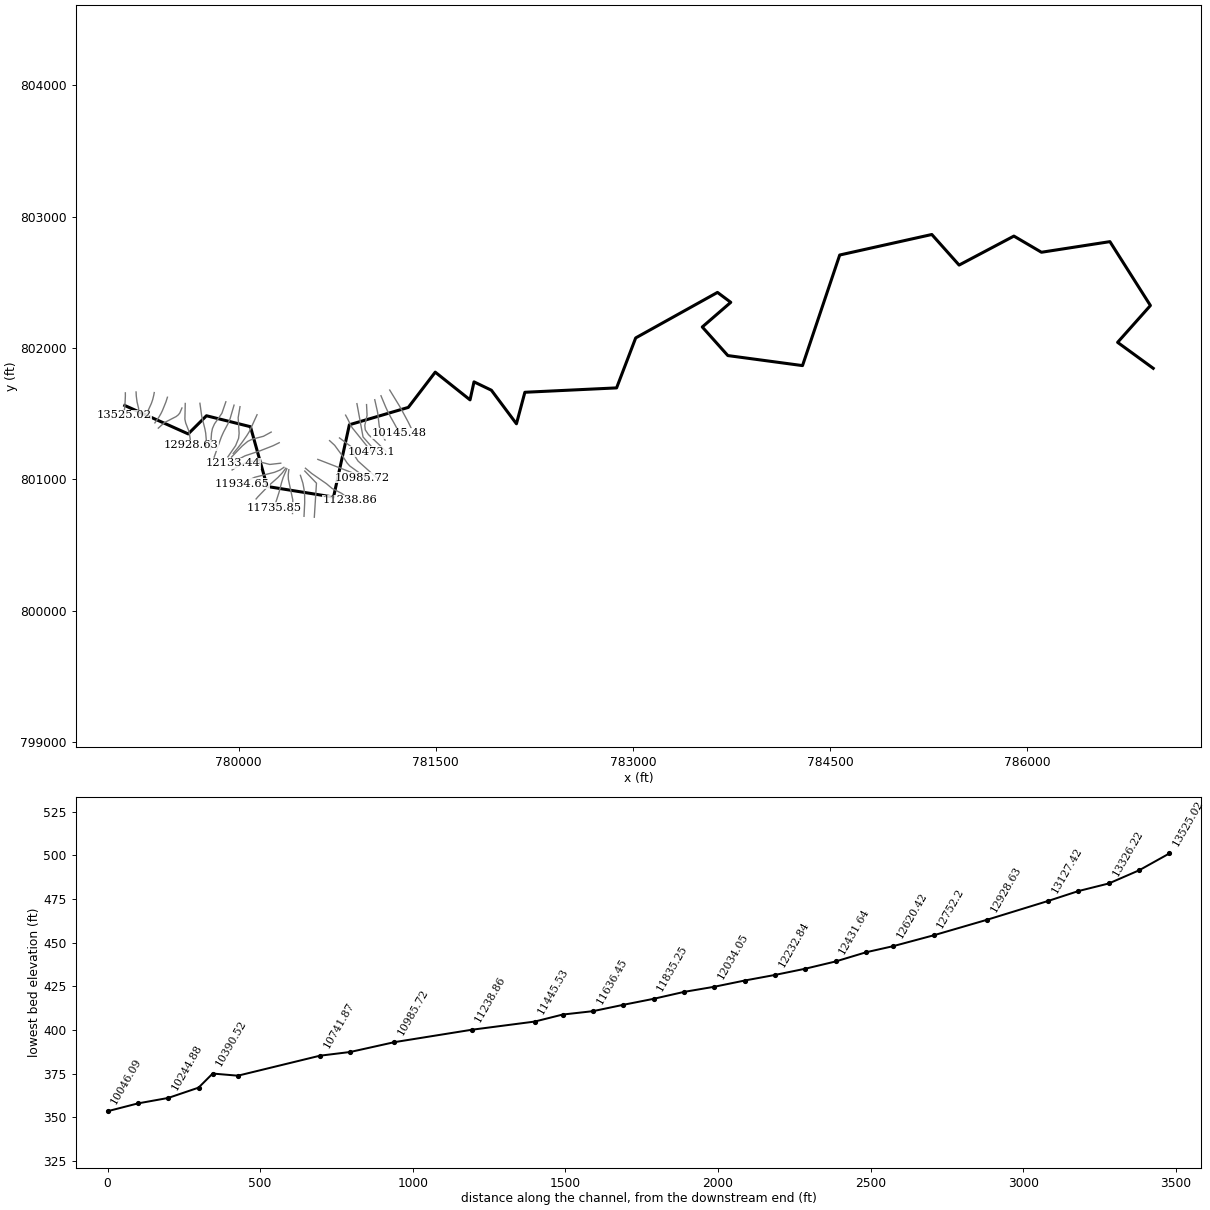
--- 17672_ras.prj (project) ---

Proj Title=17672
Current Plan=p01
Default Exp/Contr=0.3,0.1
English Units
Geom File=g01
Flow File=f01
Plan File=p01
Y Axis Title=Elevation
X Axis Title(PF)=Main Channel Distance
X Axis Title(XS)=Station
BEGIN DESCRIPTION:
RFD model 17672 exported to HEC-RAS
END DESCRIPTION:

--- 17672_ras.p01 (plan) ---

Plan Title=Plan 01
Program Version=4.10
Short Identifier=Plan 01
Geom File=g01
Flow File=f01
Subcritical Flow
Calc Critical at every XS
Secant Critical Depth

--- 17672_ras.f01 (steady flow) ---

Flow Title=Flow 01
Program Version=5.01
Number of Profiles= 6
Profile Names=10yr,25yr,50yr,100yr,100plus,500yr
River Rch & RM=17672,67,13525.02
  287.27   494.8  701.23   906.1 1322.91 2297.45
River Rch & RM=17672,67,13425.62
  288.07  496.17  703.17  908.61 1326.57 2302.92
River Rch & RM=17672,67,13326.22
  291.76  502.54  712.22  920.32 1343.66 2328.36
River Rch & RM=17672,67,13127.42
  296.23  510.26  723.19  934.49 1364.35  2359.1
River Rch & RM=17672,67,12928.63
  297.28  512.07  725.76  937.81 1369.21 2366.31
River Rch & RM=17672,67, 12752.2
  300.69  517.96  734.12  948.61 1384.98 2389.69
River Rch & RM=17672,67,12620.42
  304.09  523.82  742.45  959.39 1400.71 2412.98
River Rch & RM=17672,67,12531.04
  304.61  524.73  743.73  961.04 1403.13 2416.55
River Rch & RM=17672,67,12431.64
  308.78  531.93  753.96  974.27 1422.43 2445.08
River Rch & RM=17672,67,12232.84
  310.08  534.17  757.15  978.39 1428.45 2453.96
River Rch & RM=17672,67,12133.44
   311.9  537.31  761.61  984.16 1436.88 2466.38
River Rch & RM=17672,67,11934.65
  313.22  539.57  764.82   988.3 1442.92 2475.24
River Rch & RM=17672,67,11835.25
  376.44  649.28   921.2 1191.08 1738.97 2908.68
River Rch & RM=17672,67,11735.85
  378.72   653.2  926.76 1198.24 1749.44 2923.61
River Rch & RM=17672,67,11537.06
  379.49  654.52  928.63 1200.65 1752.95 2928.59
River Rch & RM=17672,67,11445.53
  382.28  659.32  935.43 1209.43 1765.76 2946.79
River Rch & RM=17672,67,11238.86
  386.59  666.73  945.93 1222.96 1785.52 2974.84
River Rch & RM=17672,67,10985.72
  388.38   669.8  950.27 1228.54 1793.67 2986.36
River Rch & RM=17672,67,10841.27
  391.19  674.62  957.08 1237.32 1806.48 3004.42
River Rch & RM=17672,67,10741.87
  392.72  677.24   960.8  1242.1 1813.46 3014.26
River Rch & RM=17672,67, 10473.1
  397.82  685.98  973.15    1258 1836.68 3046.96
River Rch & RM=17672,67,10244.88
  403.15  695.12  986.09 1274.66    1861 3081.14
River Rch & RM=17672,67,10046.09
  404.93  698.17   990.4  1280.2 1869.09  3092.5
River Rch & RM=17672,67,9946.688
  405.94   699.9  992.86 1283.37 1873.71 3098.99
River Rch & RM=17672,67,9648.494
   410.5  707.71  1003.9 1297.59 1894.48 3128.11
River Rch & RM=17672,67,9449.698
  411.76  709.88 1006.97 1301.53 1900.24 3136.17
River Rch & RM=17672,67,9350.299
  413.03  712.05 1010.04 1305.48 1906.01 3144.24
River Rch & RM=17672,67,9052.105
  416.07  717.26  1017.4 1314.95 1919.83 3163.55
River Rch & RM=17672,67,8753.911
  418.63  721.64 1023.58 1322.88 1931.41 3179.61
River Rch & RM=17672,67,8455.717
  441.59  760.93 1079.11 1394.29 2035.67 3324.32
River Rch & RM=17672,67,8256.921
  443.62  764.41 1084.01 1400.58 2044.84 3336.92
River Rch & RM=17672,67,8058.125
  446.93  770.04 1091.96 1410.77 2059.73 3357.36
River Rch & RM=17672,67,7859.329
  447.95  771.78  1094.4 1413.91 2064.31 3363.64
River Rch & RM=17672,67,7759.931
  457.33  787.77 1116.95 1442.84 2106.55 3421.51
River Rch & RM=17672,67,7660.533
  464.18  799.45  1133.4 1463.92 2137.33  3463.5
River Rch & RM=17672,67,7362.339
   467.2   804.6 1140.67 1473.26 2150.95 3482.09
River Rch & RM=17672,67,7163.543
  470.23  809.77 1147.95 1482.59 2164.58 3500.65
River Rch & RM=17672,67,7009.348
  473.76  815.79 1156.43 1493.47 2180.47 3522.25
River Rch & RM=17672,67,6765.951
  475.79  819.24 1161.28 1499.69 2189.55 3534.57
River Rch & RM=17672,67,6666.553
  482.67  830.92 1177.72 1520.72 2220.25 3576.03
River Rch & RM=17672,67,6467.757
  483.17  831.78 1178.93 1522.27 2222.52 3579.09
River Rch & RM=17672,67,6267.803
  483.94  833.08 1180.75 1524.61 2225.92 3583.69
River Rch & RM=17672,67,5573.174
  490.58  844.35 1196.58 1544.85 2255.47  3623.4
River Rch & RM=17672,67,5473.776
  491.09  845.21  1197.8  1546.4 2257.74 3626.45
River Rch & RM=17672,67,5374.378
  494.63  851.23 1206.27 1557.24 2273.58 3647.75
River Rch & RM=17672,67,5175.582
   496.4  854.24  1210.5 1562.66 2281.48 3658.39
River Rch & RM=17672,67,4269.407
  494.63  851.23 1206.27 1557.24 2273.58 3647.75
Boundary for River Rch & Prof#=17672,67,1
Up Type= 0
Dn Type= 2
Boundary for River Rch & Prof#=17672,67,2
Up Type= 0
Dn Type= 2
Boundary for River Rch & Prof#=17672,67,2
Up Type= 0
Dn Type= 2
Boundary for River Rch & Prof#=17672,67,2
Up Type= 0
Dn Type= 2
Boundary for River Rch & Prof#=17672,67,2
Up Type= 0
Dn Type= 2
Boundary for River Rch & Prof#=17672,67,2
Up Type= 0
Dn Type= 2

--- 17672_ras.g01 (geometry) ---

Geom Title=17672
Program Version=4.10

River Reach=17672,67
Reach XY= 30
779134.187975469801562.761889319779616.959339141801346.557360431
779755.848228069 801484.75180489780090.570450248801401.418471519
780217.653783621800946.557360413780722.695935905800865.763012016
780843.193004878801416.166258324 781291.66664833801548.260346198
781496.653150528801816.485273419781761.403783592801605.585138198
781791.612116904801742.564304882781923.903783588801679.022638232
782114.482200536801423.507556094782178.591283589801663.397638157
782876.507950249801696.730971523783021.820450275802076.939304857
 783644.21628362802423.293471525783745.257950278802347.772638192
783528.501195698802160.212709059783722.932659032801942.700164743
784291.132032931801866.326230816 784574.15127346802707.789359432
785275.094415873802863.947323351785482.618402571 802631.23352873
785899.695691467802851.800708142786109.261249335802728.783449669
786630.256025375802809.589321582786938.345384418802323.521581865
786688.716439783802043.156320221786959.767462345801845.665834478

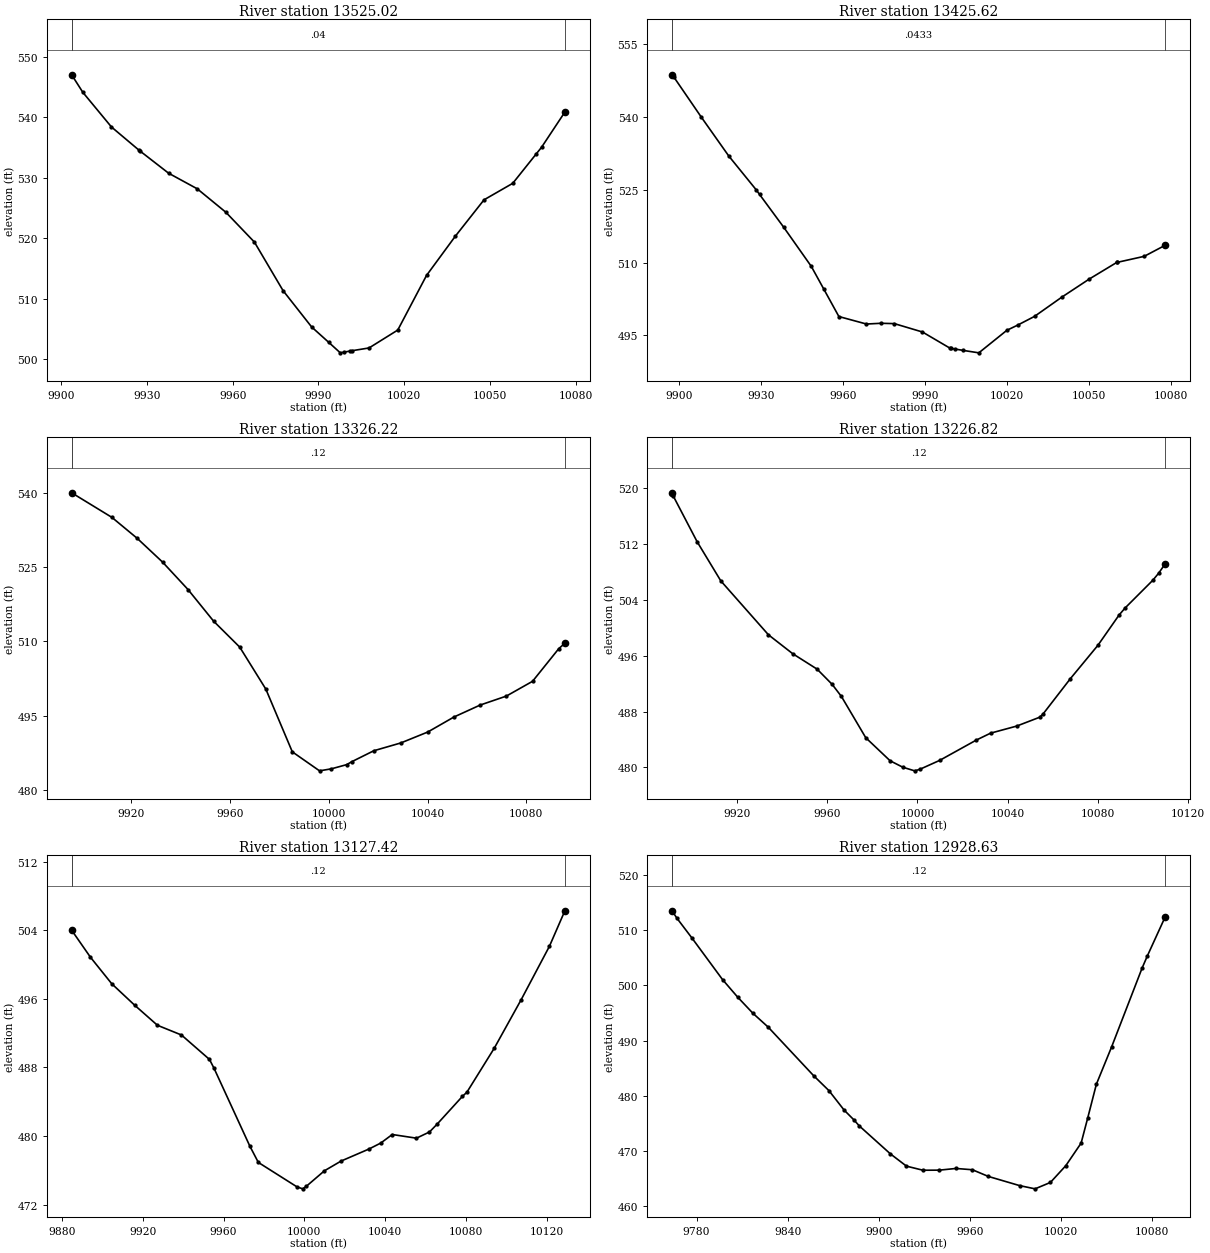
Type RM Length L Ch R = 1 ,13525.02,99.398000,99.398000,99.398000
XS GIS Cut Line= 6
779138.652078881801658.932762092779138.781809645801635.329360848
779135.844382672801569.097168234779135.075105869801561.660526685
779127.923147334801496.786200442 779126.44074173 801486.92425964
#Sta/Elev= 25
9903.623546.98779907.555544.08049917.556538.36899927.226 534.5259927.556534.3979
9937.566530.73229947.576528.15989957.586524.28969967.595519.35569977.605511.3516
9987.615505.34529993.524502.83799997.642501.0725    9999501.1918   10001501.3622
10001.69501.4189 10007.7501.877810017.76504.835810027.82513.851910037.88520.3176
10047.94526.3371   10058529.066510066.27533.953110068.07535.010210076.24540.8327
#Mann= 3 , 0 , 0
9903.623    0.04       09903.623    0.04       010076.24    0.04       0
#XS Ineff= 2 , 0
       0                               0
Bank Sta=9903.623,10076.24
Exp/Cntr=0.3,0.1

Type RM Length L Ch R = 1 ,13425.62,99.398000,99.398000,99.398000
XS GIS Cut Line= 6
779220.249070016 801665.73251136779221.920253923801633.767140351
779227.743427694801589.785073957779239.503075176801541.190184169
779241.507563034801504.840375769779239.718841725 801487.34384679
#Sta/Elev= 28
9897.477548.7476 9898.21548.22869908.224539.98269918.238531.99039928.251525.0288
9929.486524.06849938.329517.29719948.417509.2239 9952.95504.57659958.504498.8807
9968.591497.33489973.852497.48849978.778497.42089989.074495.6889    9999492.4007
9999.377 492.299   10001492.176410003.99491.892710009.68491.393510019.94496.0444
10023.85497.101610030.05498.911810040.07502.897810050.08506.6204 10060.1510.0356
10060.26510.052110070.15511.297610077.85513.5859
#Mann= 3 , 0 , 0
9897.477  0.0433       09897.477  0.0433       010077.85  0.0433       0
#XS Ineff= 2 , 0
       0                               0
Bank Sta=9897.477,10077.85
Exp/Cntr=0.3,0.1

Type RM Length L Ch R = 1 ,13326.22,99.398100,99.398100,99.398100
XS GIS Cut Line= 6
779358.481383573 801661.06627532779354.915739715801640.931801935
779346.607253439801607.216086476 779336.52439156801578.049762359
779313.273800014801527.103912641779293.906501593801472.668022248
#Sta/Elev= 22
9895.785539.99689912.101535.02759922.342 530.7999932.641  525.99 9942.94 520.455
9953.302514.06989963.882508.83299974.463500.3475 9985.18487.68879996.208483.8522
   10001484.257210007.23485.107310009.24 485.689 10018.2487.909710029.16489.4873
10040.05491.688110050.67494.721910061.28497.1341 10071.9498.946810082.51501.9335
10093.12508.5182 10095.6509.6146
#Mann= 3 , 0 , 0
9895.785    0.12       09895.785    0.12       0 10095.6    0.12       0
#XS Ineff= 2 , 0
       0                               0
Bank Sta=9895.785,10095.6
Exp/Cntr=0.3,0.1

Type RM Length L Ch R = 1 ,13226.82,99.398000,99.398000,99.398000
XS GIS Cut Line= 6
779458.798228029801625.607888627779447.363728781801589.567821659
779420.230894426801522.961610482779409.125053748801500.384548363
779394.623443568801475.537687287779363.354350742801430.462160713
#Sta/Elev= 27
9891.262519.3355  9891.9518.81949902.391512.32479912.883506.71799933.996498.9924
9944.774496.27979955.552494.07589962.218491.8958 9966.33490.15899977.108484.2529
9987.886480.95399993.524480.02819998.757479.5111   10001479.720710009.87481.0116
10026.16483.9297 10032.4 484.90610043.97485.920910054.18487.190410055.58487.6205
10067.75  492.7110079.93497.478210089.36501.8367 10092.1502.867310104.27506.8014
 10106.9507.828210109.79509.1723
#Mann= 3 , 0 , 0
9891.262    0.12       09891.262    0.12       010109.79    0.12       0
#XS Ineff= 2 , 0
       0                               0
Bank Sta=9891.262,10109.79
Exp/Cntr=0.3,0.1

Type RM Length L Ch R = 1 ,13127.42,198.796100,198.796100,198.796100
XS GIS Cut Line= 6
779569.237418363801543.916967549779552.638092833801505.031927076
779541.182999915 801491.36808552779525.251503979801478.601378191
779436.427065504801432.903207114779389.495919929801390.655680332
#Sta/Elev= 27
9884.808503.99649894.128500.83969904.666497.74959915.993495.25089927.283492.9077
9939.172491.77439953.037 488.9279955.297487.8923 9973.01478.81979977.225 476.915
9996.331474.06859999.209 473.836   10001474.136410009.92 475.93810018.18477.0751
10031.96478.475710037.83479.176210043.52480.171710055.49479.743110061.94480.4674
10065.76481.389510078.28484.628510080.48485.107910094.04490.249210107.34495.8979
10121.29502.109710128.96506.2595
#Mann= 3 , 0 , 0
9884.808    0.12       09884.808    0.12       010128.96    0.12       0
#XS Ineff= 2 , 0
       0                               0
Bank Sta=9884.808,10128.96
Exp/Cntr=0.3,0.1

Type RM Length L Ch R = 1 ,12928.63,176.425900,176.425900,176.425900
XS GIS Cut Line= 6
779594.424521491801578.253428019779591.764863359 801458.72658255
779597.594644141801430.611616136779623.260173973  801364.2876795
779631.850662986801310.632603316779635.054467274  801259.7670451
#Sta/Elev= 30
9763.823513.54239767.081512.18889777.095508.55429797.122501.06379807.136497.8687
 9817.15494.95029827.163492.45319857.185483.62339867.189480.93829877.193  477.41
9883.468475.68239887.274474.5187  9907.7 469.4649918.275467.24479929.133466.5029
9939.991466.51919950.849466.82519961.707466.5905 9972.18465.38159992.833463.7128
10002.98  463.1310013.09464.2906 10023.2467.321410033.31 471.41610037.73476.0493
10043.38482.107910053.42488.871810073.49503.158210077.01505.397810088.73512.4572
#Mann= 3 , 0 , 0
9763.823    0.12       09763.823    0.12       010088.73    0.12       0
#XS Ineff= 2 , 0
       0                               0
Bank Sta=9763.823,10088.73
Exp/Cntr=0.3,0.1

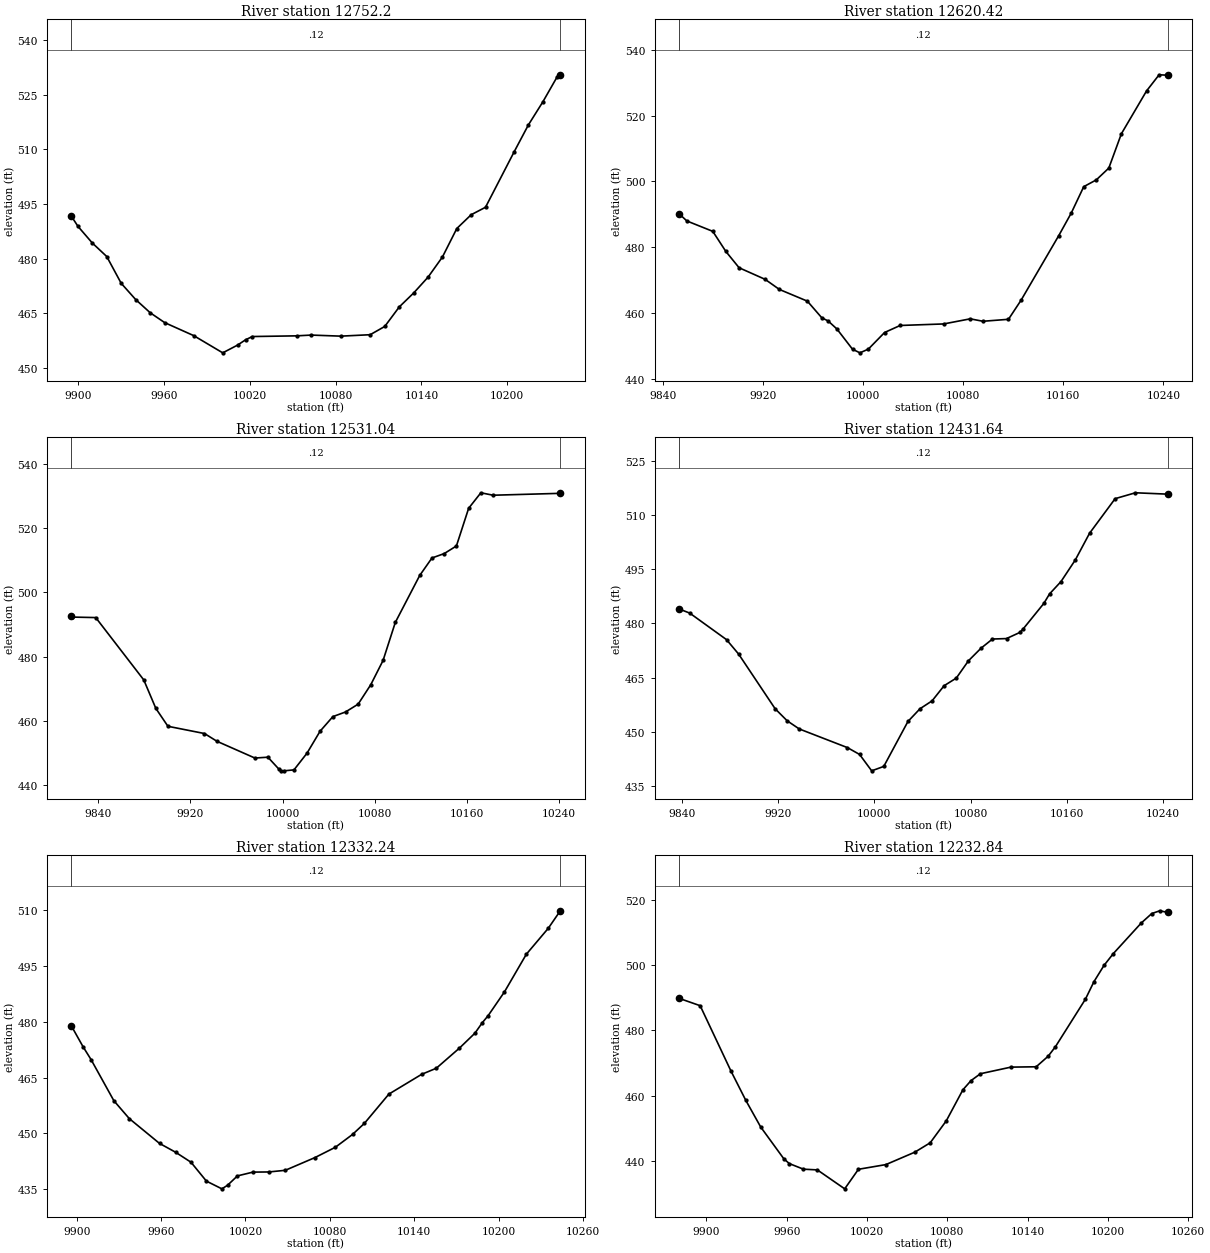
Type RM Length L Ch R = 1 , 12752.2,131.785000,131.785000,131.785000
XS GIS Cut Line= 6
779706.061546595801579.576087985779719.705024892801481.261494107
779744.146317594801383.943903934779749.932049428801352.986583924
 779754.41638311801303.273097712779752.772896616801242.750778001
#Sta/Elev= 30
9895.436491.61899900.021488.84339910.041484.27959920.114480.57679930.237473.2165
9940.361468.76119950.484465.14769960.607462.44039980.854458.879810001.17454.1509
10011.49 456.26510017.13 457.73110021.81458.623610052.75458.812210063.07459.0237
 10083.7458.7305 10104.2 459.12410114.38  461.3910124.55466.760510134.62 470.586
10144.66474.9298 10154.7480.454410164.74488.263810174.78492.043310184.79494.0918
 10204.8509.3032 10214.8516.718210224.81522.978610234.81529.848210237.06530.4392
#Mann= 3 , 0 , 0
9895.436    0.12       09895.436    0.12       010237.06    0.12       0
#XS Ineff= 2 , 0
       0                               0
Bank Sta=9895.436,10237.06
Exp/Cntr=0.3,0.1

Type RM Length L Ch R = 1 ,12620.42,89.381200,89.381200,89.381200
XS GIS Cut Line= 6
779903.437868831801591.077867302779873.216569317801503.363723846
779816.970812076801422.851237352779801.314638951801387.837609343
779794.371684292801351.903602165779785.769030676801228.027043562
#Sta/Elev= 30
9852.922490.2406 9859.21488.01429879.936484.85529890.357478.76529900.952473.8068
9921.719470.2946 9933.12467.22619955.498463.66559967.002458.62269972.086457.6521
9979.068 455.2319991.578449.06659997.481447.975310004.21449.105910017.18454.1497
10029.63456.284410064.38456.747310085.61458.2989 10095.8457.559710116.17458.1566
10126.23463.949910156.28483.523410166.29490.3861 10176.3498.422710186.32500.4783
10196.33504.065310206.38514.488410226.47527.481310236.52532.393710243.52532.2609
#Mann= 3 , 0 , 0
9852.922    0.12       09852.922    0.12       010243.52    0.12       0
#XS Ineff= 2 , 0
       0                               0
Bank Sta=9852.922,10243.52
Exp/Cntr=0.3,0.1

Type RM Length L Ch R = 1 ,12531.04,99.398000,99.398000,99.398000
XS GIS Cut Line= 6
779965.714699482801565.525282981779935.951595514801463.577686577
779919.480068706801424.252760263779885.834378381 801360.58105809
779868.670616949801322.498358307 779814.49504401801169.983093637
#Sta/Elev= 30
9816.625492.69519817.165492.32769837.735492.16879879.466 472.7469889.947463.8774
9900.427458.31699932.179456.06119943.021453.64439975.953 448.4299987.235448.6941
9996.793444.97269998.517 444.454   10001444.445510009.87444.7428 10021.2449.9504
10032.53456.774510043.65461.329610054.62462.772310065.59465.210310076.56471.2636
10087.26478.841510097.87490.6639 10119.1505.307810129.71510.730510140.32512.0945
10150.93514.469110161.54526.197310172.16531.031710182.77  530.2710241.15530.8597
#Mann= 3 , 0 , 0
9816.625    0.12       09816.625    0.12       010241.15    0.12       0
#XS Ineff= 2 , 0
       0                               0
Bank Sta=9816.625,10241.15
Exp/Cntr=0.3,0.1

Type RM Length L Ch R = 1 ,12431.64,99.398000,99.398000,99.398000
XS GIS Cut Line= 6
780011.091542166801553.701739464779997.067897379801470.131084224
780004.326120882801351.436573587780000.448762616801313.280066251
779977.531473601801257.038423576779919.030608602801172.286045985
#Sta/Elev= 30
 9837.65483.98179846.542  482.839877.133475.4887 9887.23471.48269917.521456.3806
9927.569453.03339937.569450.78879977.653  445.629987.707443.73499997.761439.2024
10007.81440.427810027.89452.854910037.93456.378610047.95458.556310057.95462.7444
10068.06464.850710078.19469.646510088.61 473.11710098.13475.653510109.78475.7792
10120.88477.476310123.62478.446810140.82485.511210145.54488.127810155.08491.5509
10166.93497.514410178.78504.896410200.04514.472710216.91516.099210243.86515.7184
#Mann= 3 , 0 , 0
 9837.65    0.12       0 9837.65    0.12       010243.86    0.12       0
#XS Ineff= 2 , 0
       0                               0
Bank Sta=9837.65,10243.86
Exp/Cntr=0.3,0.1

Type RM Length L Ch R = 1 ,12332.24,99.398100,99.398100,99.398100
XS GIS Cut Line= 6
780140.737949982801492.506194251780083.314354323801366.820843796
780063.311565945801334.173315469780025.279018237801280.015043355
779992.495280646801237.585598889779959.490168323801198.227792138
#Sta/Elev= 30
9896.296478.88669904.529 473.3199910.259469.84199926.467458.77129937.436453.9554
9958.931447.27529970.342444.90299981.311442.2096 9992.28437.123410003.28 435.044
10007.29436.000210014.35438.530610025.42439.547910036.62439.589110048.35440.0311
10069.54443.473710083.98446.2383 10096.2 449.69210104.63452.673610122.03460.5489
10145.29465.862910155.76467.510910172.12472.9017 10183.2476.941110188.47479.7736
10192.57481.643310204.23 488.075 10219.8498.216410235.36505.182910243.93509.8996
#Mann= 3 , 0 , 0
9896.296    0.12       09896.296    0.12       010243.93    0.12       0
#XS Ineff= 2 , 0
       0                               0
Bank Sta=9896.296,10243.93
Exp/Cntr=0.3,0.1

Type RM Length L Ch R = 1 ,12232.84,99.398000,99.398000,99.398000
XS GIS Cut Line= 6
780248.370204578801360.577286654780189.645048497801328.599212084
780104.624456823801306.457990304780070.175434421 801289.97357939
780027.678801191801254.572099609779946.653658935801170.677518674
#Sta/Elev= 30
9879.506489.83079895.328487.5651 9918.39467.51199929.472  458.549940.555450.4154
9957.825440.67889961.933439.20889972.479437.49719982.874437.274810003.31431.4744
10013.57437.463810034.08438.900310055.68442.701810067.19445.575110079.19452.2926
10091.64461.822710097.71 464.62910104.73466.730110127.48468.751510146.37468.8572
10155.33472.096110160.76475.011510183.13489.548610189.55494.939710197.03499.8981
10203.94503.495410224.84512.880110232.73515.791210238.74 516.63610244.75516.1262
#Mann= 3 , 0 , 0
9879.506    0.12       09879.506    0.12       010244.75    0.12       0
#XS Ineff= 2 , 0
       0                               0
Bank Sta=9879.506,10244.75
Exp/Cntr=0.3,0.1

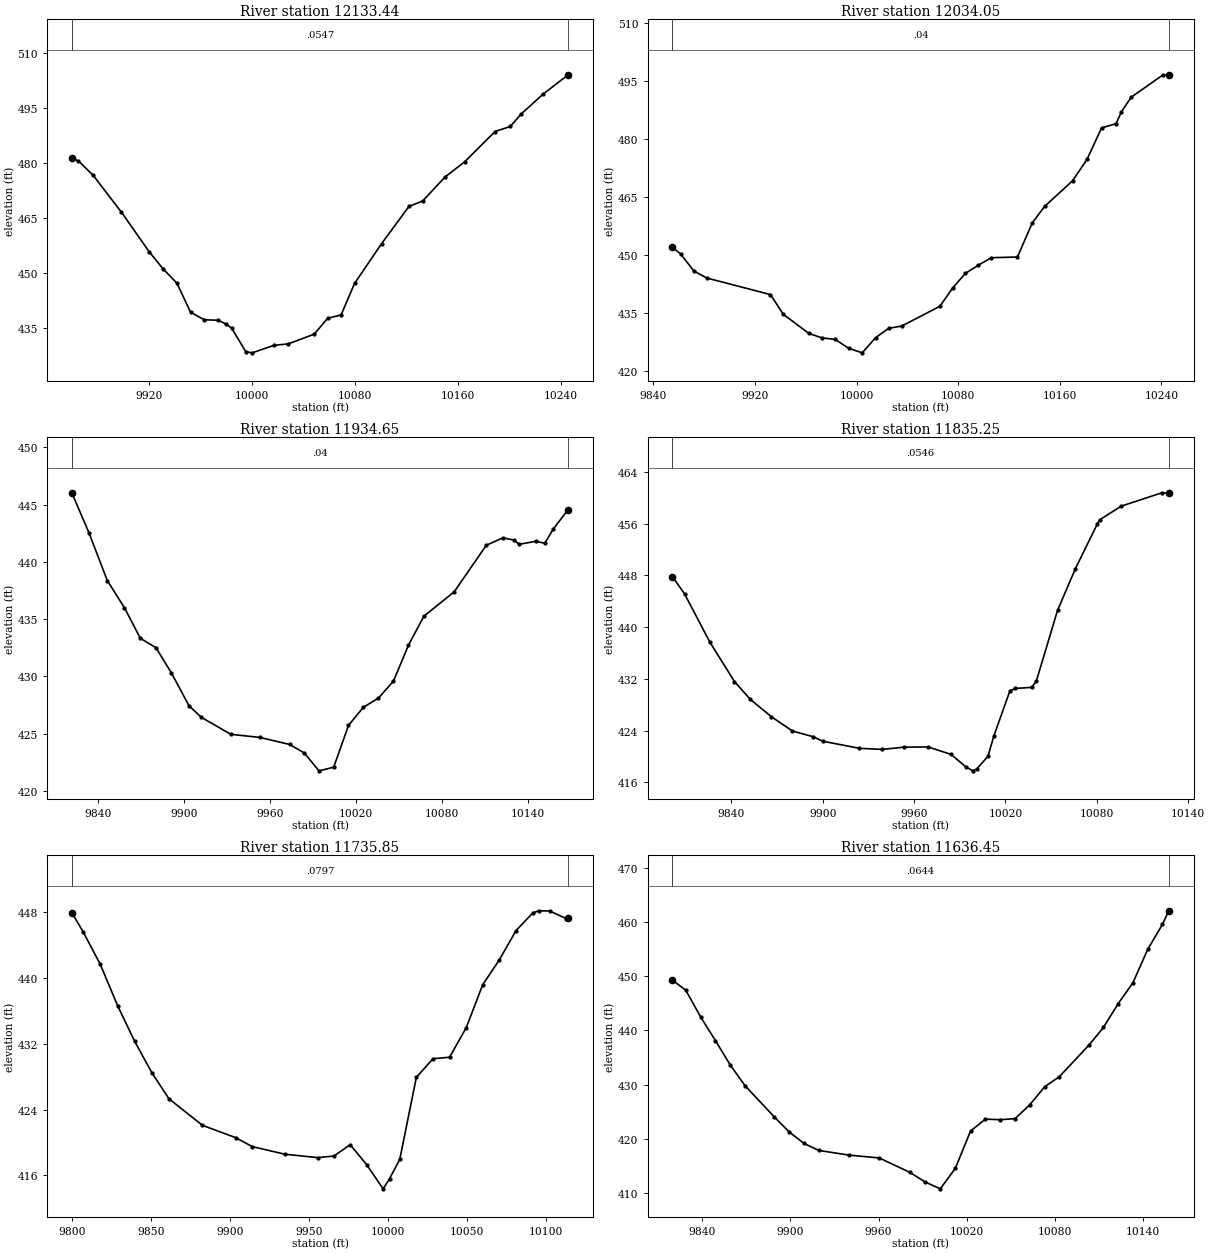
Type RM Length L Ch R = 1 ,12133.44,99.398000,99.398000,99.398000
XS GIS Cut Line= 6
780309.456240065801279.702817109 780262.51137917 801256.62966304
 780163.77979304801217.989892869780049.413289664801179.950523837
 779999.22146293801153.076920967779958.585965276801123.540808393
#Sta/Elev= 30
9859.766481.34139864.974480.56139876.381476.66079898.391   466.69920.152455.7352
9930.825451.13549941.499447.28669952.173439.33249962.846437.2803 9973.52437.1551
9980.097 436.0739984.267434.92919995.131428.573110000.13428.268810016.86 430.297
10028.19430.721410048.34433.349810058.82 437.676 10069.3438.604310079.78447.2146
10100.73457.998410122.05468.172310132.77469.669110150.16 476.21110165.29480.2961
10189.05488.593810200.96489.978310209.48 493.40210226.48498.799910245.97504.0603
#Mann= 3 , 0 , 0
9859.766  0.0547       09859.766  0.0547       010245.97  0.0547       0
#XS Ineff= 2 , 0
       0                               0
Bank Sta=9859.766,10245.97
Exp/Cntr=0.3,0.1

Type RM Length L Ch R = 1 ,12034.05,99.398100,99.398100,99.398100
XS GIS Cut Line= 6
780321.122727266801123.729524871780237.471077041801114.215505535
780146.048527543801138.043848377780093.905085672801138.172304646
780022.090242935801116.550251566779951.028687332801072.204559512
#Sta/Elev= 30
9854.888452.00779861.328450.32779871.936445.87129881.959444.08249932.194439.7835
9942.231 434.6899962.526429.71489972.673428.58799983.197428.1689 9993.77425.8858
 10004.4424.7057   10015428.637710025.27431.056210035.52431.629810065.61436.7529
10075.64441.476810085.66445.260310095.88447.380610106.12449.324510126.71449.5094
10138.39458.357410148.13462.615210170.07 469.23310181.51474.780210192.94482.9119
10204.38484.028610208.65487.135410216.36490.887610240.98496.565510245.86496.6772
#Mann= 3 , 0 , 0
9854.888    0.04       09854.888    0.04       010245.86    0.04       0
#XS Ineff= 2 , 0
       0                               0
Bank Sta=9854.888,10245.86
Exp/Cntr=0.3,0.1

Type RM Length L Ch R = 1 ,11934.65,99.398000,99.398000,99.398000
XS GIS Cut Line= 6
780345.158788011801092.388945612780314.398448266 801071.14903489
780273.361991423801054.507992329780125.594920117801017.230261757
780058.137188965800986.378157907780026.066140459800966.328729003
#Sta/Elev= 30
9821.693 446.034 9833.66442.5415  9846.5438.35949858.416435.9983 9869.47433.3316
9880.469432.50059891.158430.30679903.467427.43869912.047426.43059932.568424.9466
9953.089424.6678 9973.61424.0588 9983.87423.3191 9994.13 421.75410004.41422.0704
10014.72 425.71810025.09427.302410035.59428.099710046.08 429.58310056.59432.7281
10067.35435.257110088.48437.386910110.88  441.4510122.52442.100210130.19441.8978
10133.89 441.53610145.67441.8014 10151.7 441.62110157.46442.848510168.02444.5666
#Mann= 3 , 0 , 0
9821.693    0.04       09821.693    0.04       010168.02    0.04       0
#XS Ineff= 2 , 0
       0                               0
Bank Sta=9821.693,10168.02
Exp/Cntr=0.3,0.1

Type RM Length L Ch R = 1 ,11835.25,99.398000,99.398000,99.398000
XS GIS Cut Line= 6
780359.358494161801085.465121952780333.120024364801050.379811008
780299.574259996801014.988904473780226.953203672800950.557210706
780147.191782704800867.988278484780133.483118535800851.585948616
#Sta/Elev= 30
9801.293447.82039809.304 445.146 9825.91437.68639842.096431.58989852.552 428.827
 9866.33426.15889880.108423.95619893.887423.05759900.017422.37719924.021421.2817
9939.089421.10799953.491421.45869969.224421.48699984.292420.33719993.853418.4274
9998.578 417.799   10001418.057810008.49420.045310012.36423.184110022.84430.1212
 10026.3430.524710037.19430.694210040.25431.661510054.19442.601810065.89449.0334
10080.24455.919210082.08456.623110096.02458.698110122.72460.758310127.17460.6833
#Mann= 3 , 0 , 0
9801.293  0.0546       09801.293  0.0546       010127.17  0.0546       0
#XS Ineff= 2 , 0
       0                               0
Bank Sta=9801.293,10127.17
Exp/Cntr=0.3,0.1

Type RM Length L Ch R = 1 ,11735.85,99.398100,99.398100,99.398100
XS GIS Cut Line= 6
780367.608644356801081.442321444780339.656117386 801015.37608561
780327.478592333800976.950827752780308.088584254800902.260274806
780282.163860176800821.314126349780268.725284258800783.964865754
#Sta/Elev= 30
9800.076447.9268 9807.14445.62789818.104441.63349829.069436.60889839.867432.2735
9850.655428.49289861.443 425.316 9882.71422.0757 9903.69420.58489914.149419.4967
9934.812418.56679955.475418.15249965.807418.34529976.138419.7248 9986.47417.3172
9996.951414.3604   10001415.588110007.48417.941410017.97427.912610028.47430.1686
10038.96430.352910049.45433.921310059.94439.166610070.43442.184710081.01445.7455
10091.64447.896510095.46448.150710102.26448.120310112.89447.192910113.99447.2464
#Mann= 3 , 0 , 0
9800.076  0.0797       09800.076  0.0797       010113.99  0.0797       0
#XS Ineff= 2 , 0
       0                               0
Bank Sta=9800.076,10113.99
Exp/Cntr=0.3,0.1

Type RM Length L Ch R = 1 ,11636.45,99.398000,99.398000,99.398000
XS GIS Cut Line= 6
780382.616890995801074.124250769780378.000797662801034.969701833
780379.171634569801000.217300146780412.325571507800846.298580121
780413.834715015 800782.91909299780410.695848821800740.696059551
#Sta/Elev= 30
9819.703449.32099828.891447.4329 9838.96442.49869849.029 438.1229859.099433.6219
9869.105 429.8069889.116424.00499899.168 421.2549909.262419.11639919.357417.8244
 9939.82416.96289960.382416.43949981.167413.78539991.559412.012510001.94 410.726
10012.24414.535410022.53421.408610032.67423.616210042.78423.503610052.88423.7074
10062.91426.279510072.93429.591510082.94431.452610102.94437.251610112.94440.5595
10122.96444.961610132.99448.810810143.02454.978510153.04459.603210157.36462.1318
#Mann= 3 , 0 , 0
9819.703  0.0644       09819.703  0.0644       010157.36  0.0644       0
#XS Ineff= 2 , 0
       0                               0
Bank Sta=9819.703,10157.36
Exp/Cntr=0.3,0.1

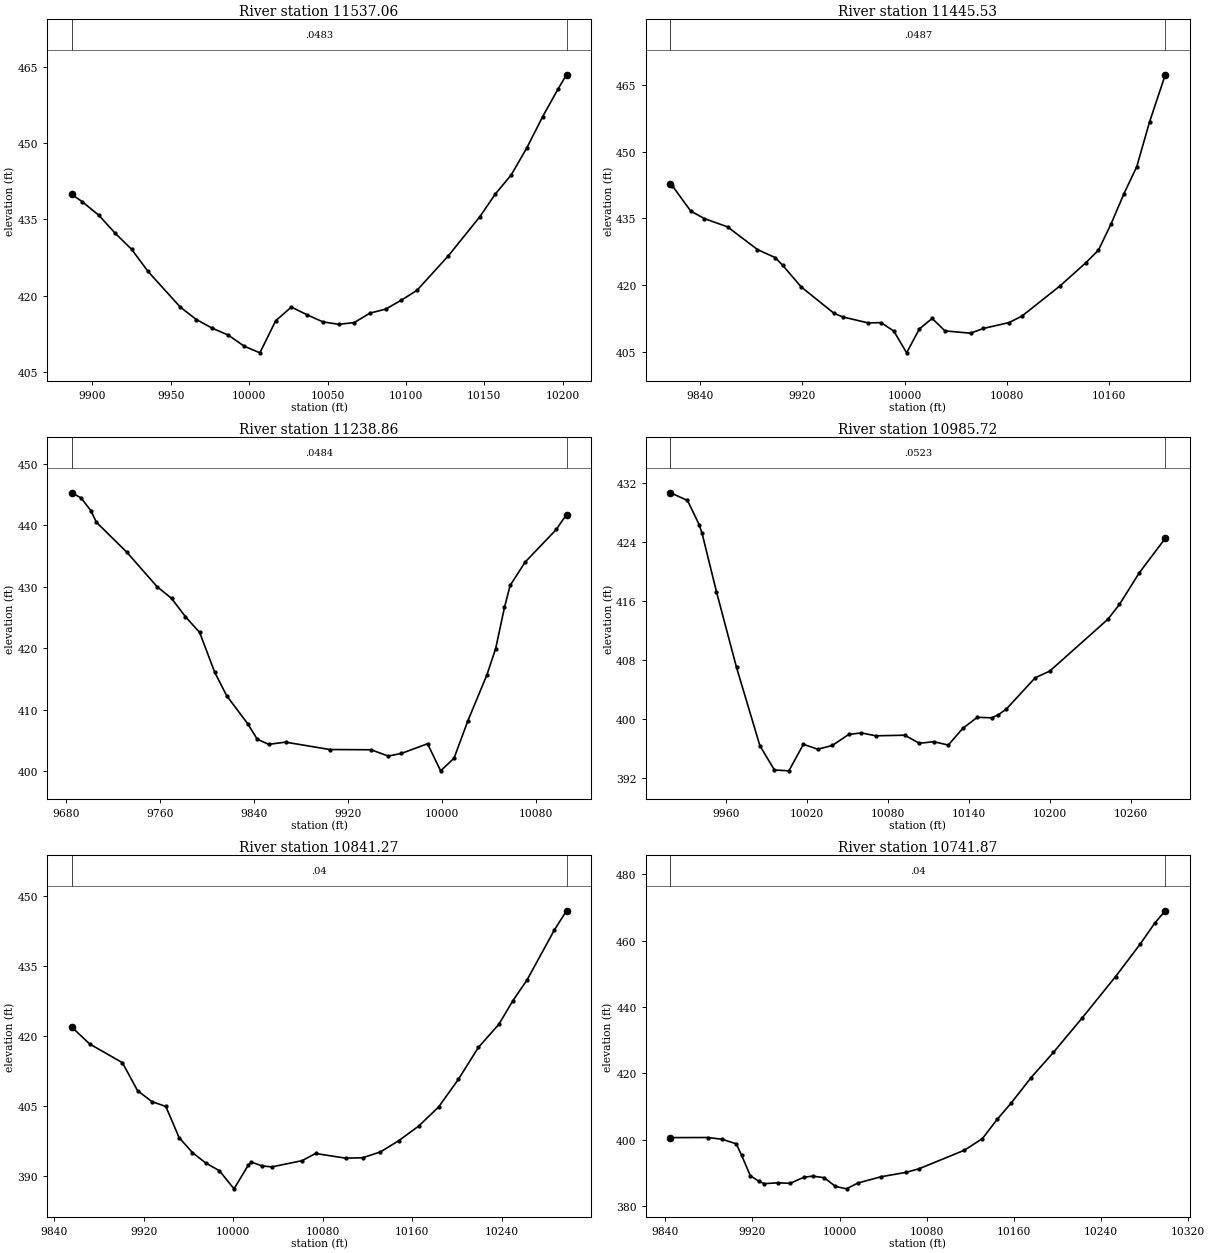
Type RM Length L Ch R = 1 ,11537.06,91.522600,91.522600,91.522600
XS GIS Cut Line= 6
780470.676836708801031.185930134 780489.69244824800971.067417027
780498.220902459800925.389453924780502.771720521800877.367132239
780503.297436455800822.371424355780498.105373375 800719.75964648
#Sta/Elev= 30
 9886.87439.91299893.472438.49899904.143435.81069914.743432.23049925.127429.1014
9935.511424.7694 9956.15417.75559966.323415.32559976.496413.61849986.669412.2713
9996.837410.088810006.89408.776310016.93415.067910026.97417.771910037.02416.2457
10047.05414.865810057.05414.379110067.05414.717310077.05416.575710087.05417.3617
10097.05419.108910107.06421.059810127.08427.8356 10147.1435.501510157.11440.0178
10167.12443.705110177.13449.041210187.16455.154510197.18460.693110202.43463.4066
#Mann= 3 , 0 , 0
 9886.87  0.0483       0 9886.87  0.0483       010202.43  0.0483       0
#XS Ineff= 2 , 0
       0                               0
Bank Sta=9886.87,10202.43
Exp/Cntr=0.3,0.1

Type RM Length L Ch R = 1 ,11445.53,206.671500,206.671500,206.671500
XS GIS Cut Line= 3
780503.985035092801064.116950399780592.862248003800971.731426409
780576.490129858800712.701128161
#Sta/Elev= 30
9816.546442.6997 9818.01 442.3379832.434 436.6499843.073434.97479861.282433.1006
9884.702 428.0069898.578426.19169904.554424.43389918.978419.59619944.743413.6454
9951.487412.84719971.527 411.4939981.547411.56369991.567409.664310001.59404.7646
10011.61410.150410021.63 412.50510031.65409.702710051.69409.181310061.71 410.247
10081.75411.568810091.77412.981910121.83419.824210141.87424.981710151.89 427.839
10161.91433.823610171.93440.567910181.95446.640810191.97456.708810204.29467.3145
#Mann= 3 , 0 , 0
9816.546  0.0487       09816.546  0.0487       010204.29  0.0487       0
#XS Ineff= 2 , 0
       0                               0
Bank Sta=9816.546,10204.29
Exp/Cntr=0.3,0.1

Type RM Length L Ch R = 1 ,11238.86,253.144500,253.144500,253.144500
XS GIS Cut Line= 6
780508.921213209801085.505444547780556.344556597801045.648885684
780668.855990474800967.651455208780711.932340959800931.472147877
780785.301029777 800893.91146852780851.275129896800842.206786453
#Sta/Elev= 30
 9684.61445.27819692.551444.44279700.939 442.3769705.613 440.4929731.739435.5831
9757.282430.02059769.673428.10459781.529425.11989793.611422.57659806.489416.0719
9816.639412.28369834.536407.73229842.662405.21459852.434404.36959866.777404.7297
9904.567403.52879939.738403.48849954.322 402.4649965.482402.89339987.801404.4703
9998.961400.063210010.36402.114410022.19408.209910038.27415.612310045.85419.9289
10053.35426.628910058.16430.202910070.97434.011110097.48439.307110106.21441.7444
#Mann= 3 , 0 , 0
 9684.61  0.0484       0 9684.61  0.0484       010106.21  0.0484       0
#XS Ineff= 2 , 0
       0                               0
Bank Sta=9684.61,10106.21
Exp/Cntr=0.3,0.1

Type RM Length L Ch R = 1 ,10985.72,144.447600,144.447600,144.447600
XS GIS Cut Line= 3
780603.261398643801152.657610238780913.146455759801032.580879553
780942.037039698801014.841644354
#Sta/Elev= 30
9918.947430.64889931.536429.61069940.141426.34149942.261425.19999952.985417.2372
9967.818406.98699985.159396.36049995.883393.082710006.61392.966910017.33396.5637
10028.06 395.89110038.78396.415510050.85397.893410060.23398.110910070.95397.7149
 10092.4397.796410103.13396.699910113.85396.914710124.58396.4582 10135.3398.7224
10146.03400.217510156.75400.152310161.56400.558610167.47401.319610188.92405.5822
10199.65406.477910242.55  413.4810251.28415.514510265.77 419.75710285.19424.4743
#Mann= 3 , 0 , 0
9918.947  0.0523       09918.947  0.0523       010285.19  0.0523       0
#XS Ineff= 2 , 0
       0                               0
Bank Sta=9918.947,10285.19
Exp/Cntr=0.3,0.1

Type RM Length L Ch R = 1 ,10841.27,99.398000,99.398000,99.398000
XS GIS Cut Line= 6
 780692.64249554801295.498453842780731.127844523801260.158092593
780796.115606231801171.487290361780825.729475848801125.695531184
780846.523869887801102.471996635781003.301692949800988.397021962
#Sta/Elev= 30
9855.793421.91229871.875418.2926  9901.1414.3019 9914.67 408.3029927.459405.9922
9939.877404.94339951.782398.27989963.687395.08919975.593392.85439987.743391.2198
10000.81387.347210013.66392.4512 10016.4393.0442 10025.9392.246110034.53392.0336
10061.63393.367910073.64394.901610100.49393.902910115.71393.989610131.55 395.224
10148.01397.638910165.78400.752510183.56404.828410201.19 410.71710219.11417.5578
10237.47422.512810249.94427.544810262.46 431.917 10286.9442.594210297.88446.7637
#Mann= 3 , 0 , 0
9855.793    0.04       09855.793    0.04       010297.88    0.04       0
#XS Ineff= 2 , 0
       0                               0
Bank Sta=9855.793,10297.88
Exp/Cntr=0.3,0.1

Type RM Length L Ch R = 1 ,10741.87,268.771500,268.771500,268.771500
XS GIS Cut Line= 6
780768.060230166801315.998045042780861.619641962801245.679301021
780870.504086382801232.567203814780884.554877197801178.366779932
780909.190632484801139.907146524781072.033903285800994.130369861
#Sta/Elev= 30
9844.823 400.6559879.462400.68649892.319400.14869905.177398.78169910.046395.3809
9918.035389.19259925.954 387.4799930.893386.7725 9943.32387.03379954.647386.8708
9967.378388.72639975.547389.04999985.952388.55729996.159385.958110006.39385.2143
10016.69386.959710038.17388.867710061.34390.198610073.06391.2851 10114.6396.8641
10131.05400.360110144.57406.133710157.19410.964110175.75418.746910196.29426.3656
10222.52436.691210253.32 449.22410275.71458.932710289.31465.360410298.87469.0364
#Mann= 3 , 0 , 0
9844.823    0.04       09844.823    0.04       010298.87    0.04       0
#XS Ineff= 2 , 0
       0                               0
Bank Sta=9844.823,10298.87
Exp/Cntr=0.3,0.1

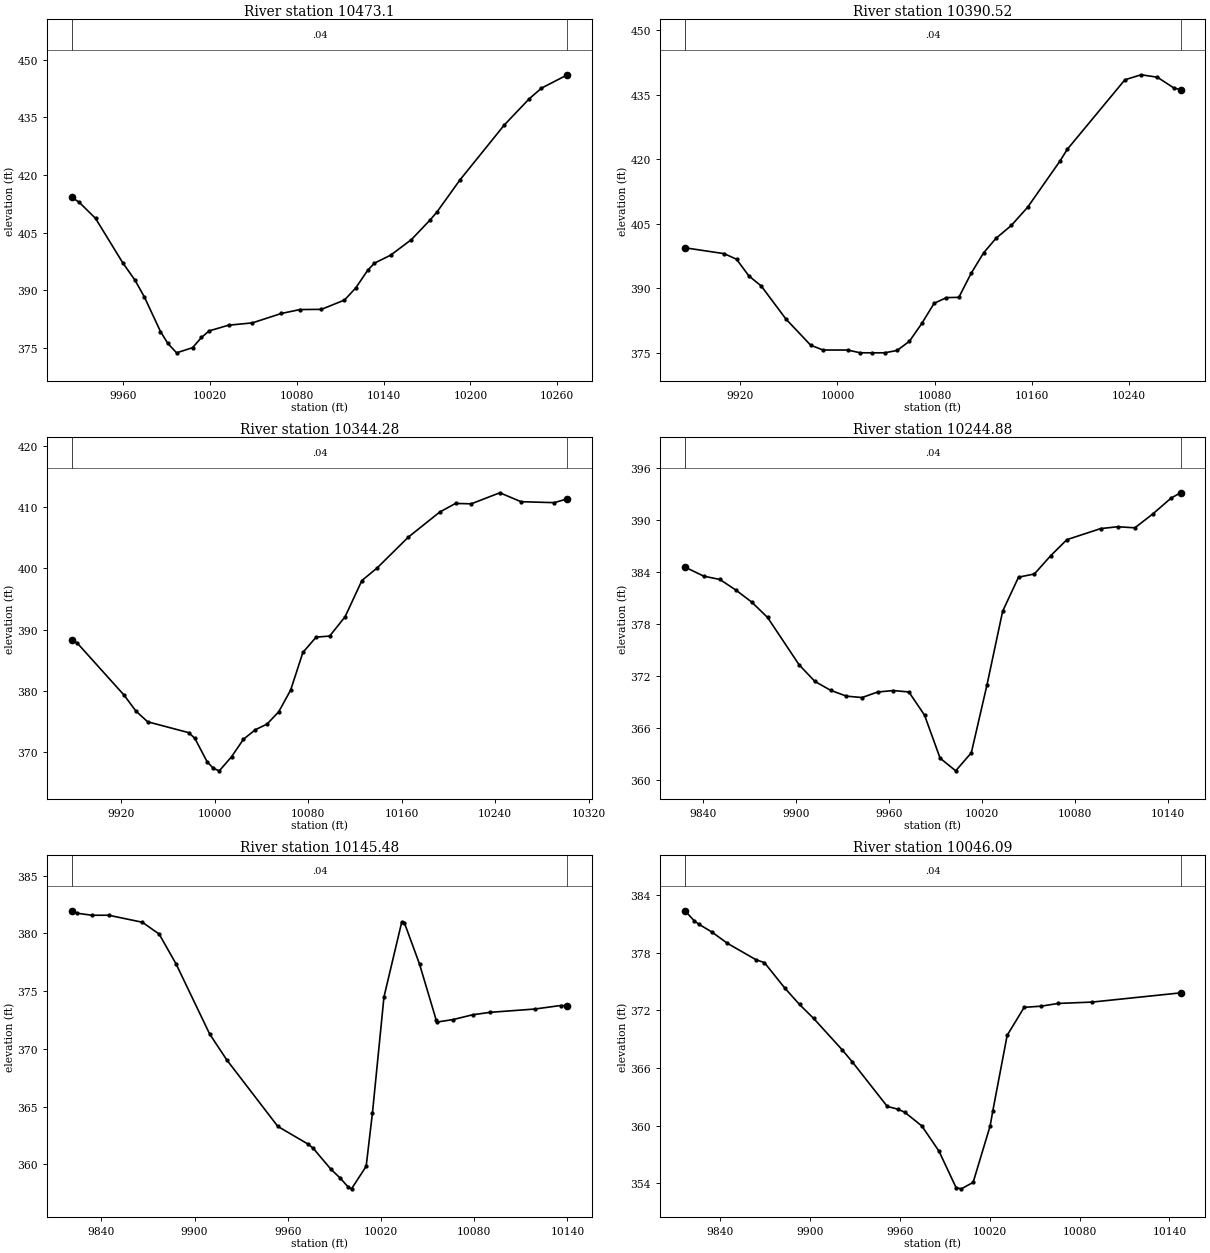
Type RM Length L Ch R = 1 , 10473.1,82.582900,82.582900,82.582900
XS GIS Cut Line= 6
780814.558825474 801489.45567839780831.268876156801458.418020672
780854.901116776801409.596537286780868.226173349801388.589747174
780876.918445005801378.381038977781011.612485677801210.993479803
#Sta/Elev= 30
9924.425414.21179929.485412.93939940.842408.73269959.675397.17279968.147392.6476
 9974.62388.29379985.758379.30529990.854376.20619996.878373.768410007.93375.1123
 10014.1377.769510019.36379.471110032.77380.951810049.25381.556610069.38384.0112
10082.22385.0201   10097385.074310112.95387.494610120.72390.6359 10128.9 395.194
10133.56397.063110144.85399.163610159.23403.216110172.06408.294610176.75410.3271
 10192.7418.693210223.41433.006710240.56439.784110249.08 442.57810267.06446.0604
#Mann= 3 , 0 , 0
9924.425    0.04       09924.425    0.04       010267.06    0.04       0
#XS Ineff= 2 , 0
       0                               0
Bank Sta=9924.425,10267.06
Exp/Cntr=0.3,0.1

Type RM Length L Ch R = 1 ,10390.52,46.237700,46.237700,46.237700
XS GIS Cut Line= 3
780900.793030888801576.789297864780947.293450028801323.276430637
781046.841775656801210.609333351
#Sta/Elev= 30
9874.495399.42159906.815398.05819916.982396.75239927.149392.87039937.316390.5369
9957.649382.84999977.983376.7746 9988.15375.654210008.48375.643810018.65375.0132
10028.82374.994510038.98375.010210049.15375.545710059.32377.696210069.48381.8223
10079.65386.520210089.82387.835910099.98387.899710110.15393.498110120.32398.2231
10130.49 401.60210143.28404.640810156.63 408.85810183.31419.619510189.19422.2914
10236.69 438.48610250.04439.652210263.38439.090110276.72 436.63910282.58436.1447
#Mann= 3 , 0 , 0
9874.495    0.04       09874.495    0.04       010282.58    0.04       0
#XS Ineff= 2 , 0
       0                               0
Bank Sta=9874.495,10282.58
Exp/Cntr=0.3,0.1

Type RM Length L Ch R = 1 ,10344.28,99.398100,99.398100,99.398100
XS GIS Cut Line= 6
780973.877432832 801569.63268637780977.959410778801488.429545992
780960.601502768 801412.04634063780964.177867761801377.512343801
780988.369361931801341.426155187781123.019841081 801213.93436262
#Sta/Elev= 30
 9877.74388.29319882.443387.80569922.689379.2542 9932.71376.67039942.721374.9347
9977.925373.15689983.124372.21559993.539368.4175    9999  367.3110004.01366.9192
10014.48369.220510024.68372.084110034.82373.635410044.86374.561510054.86 376.573
10065.07380.125910075.55386.276610086.85388.773310098.46388.950810111.71392.1267
10126.04398.032110138.84400.041710165.77405.123710192.71409.229310206.18410.6279
10219.64410.568510244.09 412.37210262.16410.916810290.56410.755310301.94411.3849
#Mann= 3 , 0 , 0
 9877.74    0.04       0 9877.74    0.04       010301.94    0.04       0
#XS Ineff= 2 , 0
       0                               0
Bank Sta=9877.74,10301.94
Exp/Cntr=0.3,0.1

Type RM Length L Ch R = 1 ,10244.88,99.398000,99.398000,99.398000
XS GIS Cut Line= 6
 781036.38819273801606.616443246781058.178921293801510.128954671
781070.417751734801406.937381548781075.436514836801383.993653347
781098.213484261801326.826348795 781114.68367543 801299.81800032
#Sta/Elev= 30
 9828.52 384.5239840.631383.47799851.057 383.0949861.372381.87189871.569380.4886
9881.766378.72129902.159373.24999912.356371.33039922.552370.30259932.683369.6368
 9942.75369.47779952.817370.11539962.884370.28479972.951 370.1189983.019367.4489
9993.086362.481910003.15361.023110013.23363.112610023.31370.930510033.42 379.435
10043.66383.359110053.89383.729410064.36385.827210074.85387.686310096.59388.9608
10107.58 389.17610118.71389.053610130.42390.673810142.14392.494810148.21393.0931
#Mann= 3 , 0 , 0
 9828.52    0.04       0 9828.52    0.04       010148.21    0.04       0
#XS Ineff= 2 , 0
       0                               0
Bank Sta=9828.52,10148.21
Exp/Cntr=0.3,0.1

Type RM Length L Ch R = 1 ,10145.48,99.398000,99.398000,99.398000
XS GIS Cut Line= 6
781083.753674499801636.930351577781118.789985918801552.707385143
781136.300235374801514.214937002781157.410545717801474.961165351
781190.261583347801416.292025782781224.837064103801351.143952024
#Sta/Elev= 30
9820.922381.95849824.167381.74969833.843381.57279844.674381.57289866.336 380.966
9877.166379.94289887.997 377.3749909.659371.29889920.609369.06639953.567363.2919
9972.798361.77579976.247361.41249987.602359.60319993.911358.79129998.956 358.031
   10001357.886310010.43359.8348 10014.5364.478110021.89374.495110033.35380.9908
10034.98380.9393 10044.8377.334210055.46372.522810056.26372.330310066.24372.5357
10079.02372.956410090.35373.167810119.01373.452810135.63373.7579   10140373.7467
#Mann= 3 , 0 , 0
9820.922    0.04       09820.922    0.04       0   10140    0.04       0
#XS Ineff= 2 , 0
       0                               0
Bank Sta=9820.922,10140
Exp/Cntr=0.3,0.1

Type RM Length L Ch R = 1 ,10046.09,99.398100,99.398100,99.398100
XS GIS Cut Line= 6
781150.190456054801680.274026969781224.321690265801559.109272382
781244.053634849801523.712800993781245.003152083  801521.9525689
781290.382775918801437.855918107781312.837730181801392.147846607
#Sta/Elev= 28
9816.432382.35239822.615381.31449825.647380.96089834.338380.14949844.808378.9639
 9863.97377.24969869.507376.95879883.131374.30439892.954372.59829902.292371.1613
9921.453367.88019928.123366.64069951.569361.98699958.475361.7095 9963.18361.3864
9974.629359.95749986.077357.33959997.526353.534810000.99 353.411 10008.9354.0813
10020.26359.961710022.05361.525110031.63369.387810042.99372.301510054.35372.4237
10065.72372.708710088.44372.850110147.49373.8091
#Mann= 3 , 0 , 0
9816.432    0.04       09816.432    0.04       010147.49    0.04       0
#XS Ineff= 2 , 0
       0                               0
Bank Sta=9816.432,10147.49
Exp/Cntr=0.3,0.1