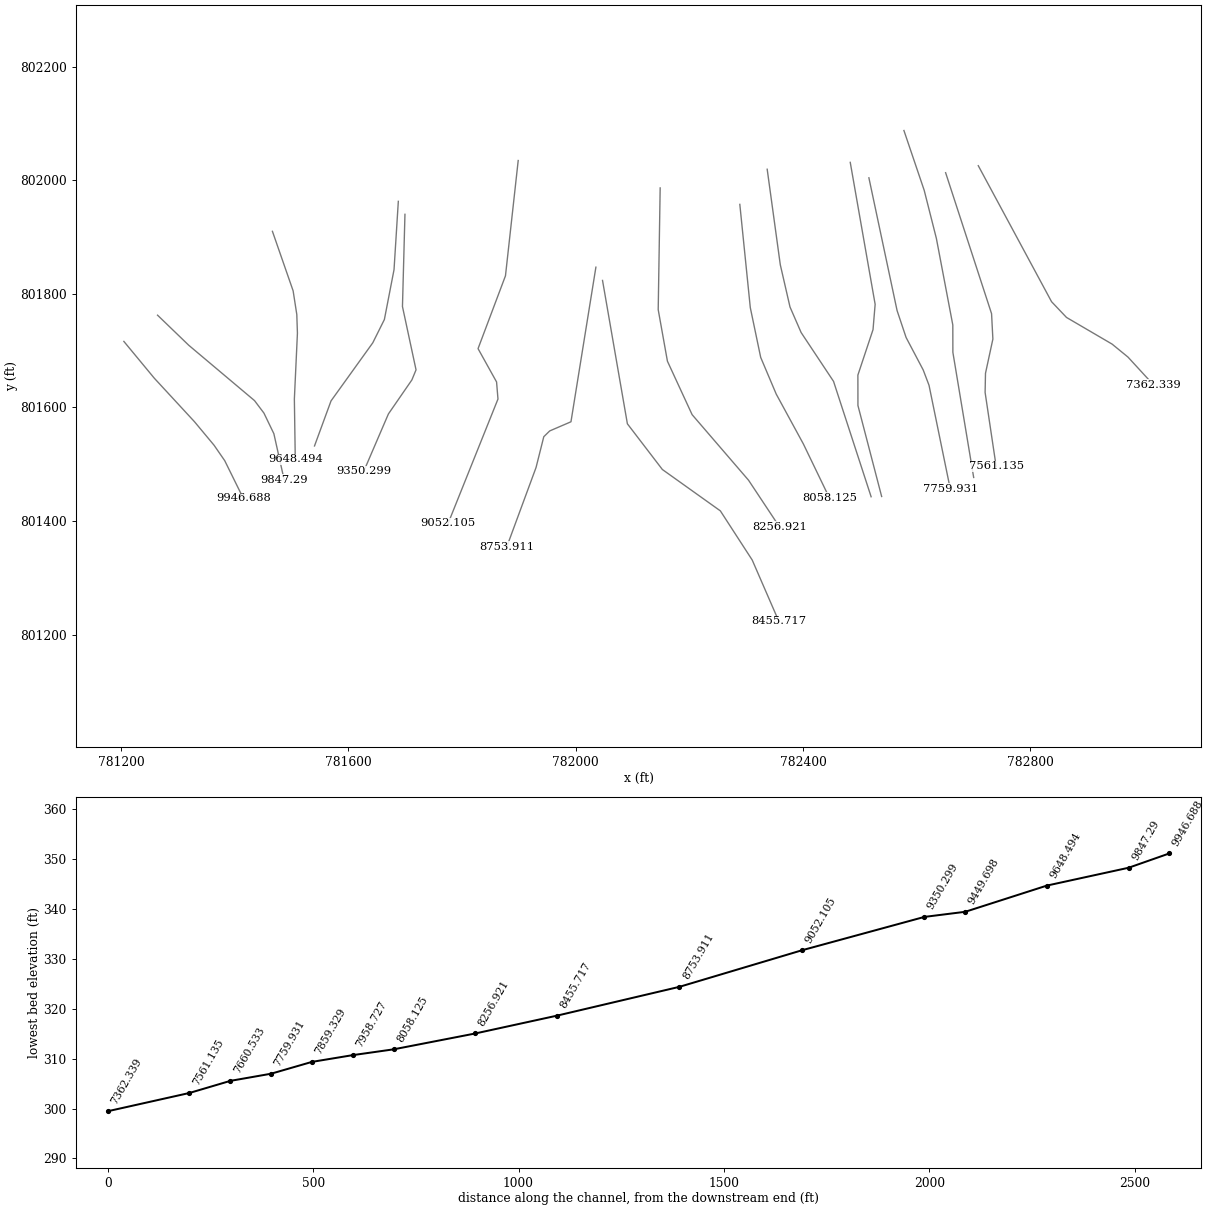
HEC-RAS study 17672_ras.prj: 17672

--- 17672_ras.g01 (geometry) --- (continued)

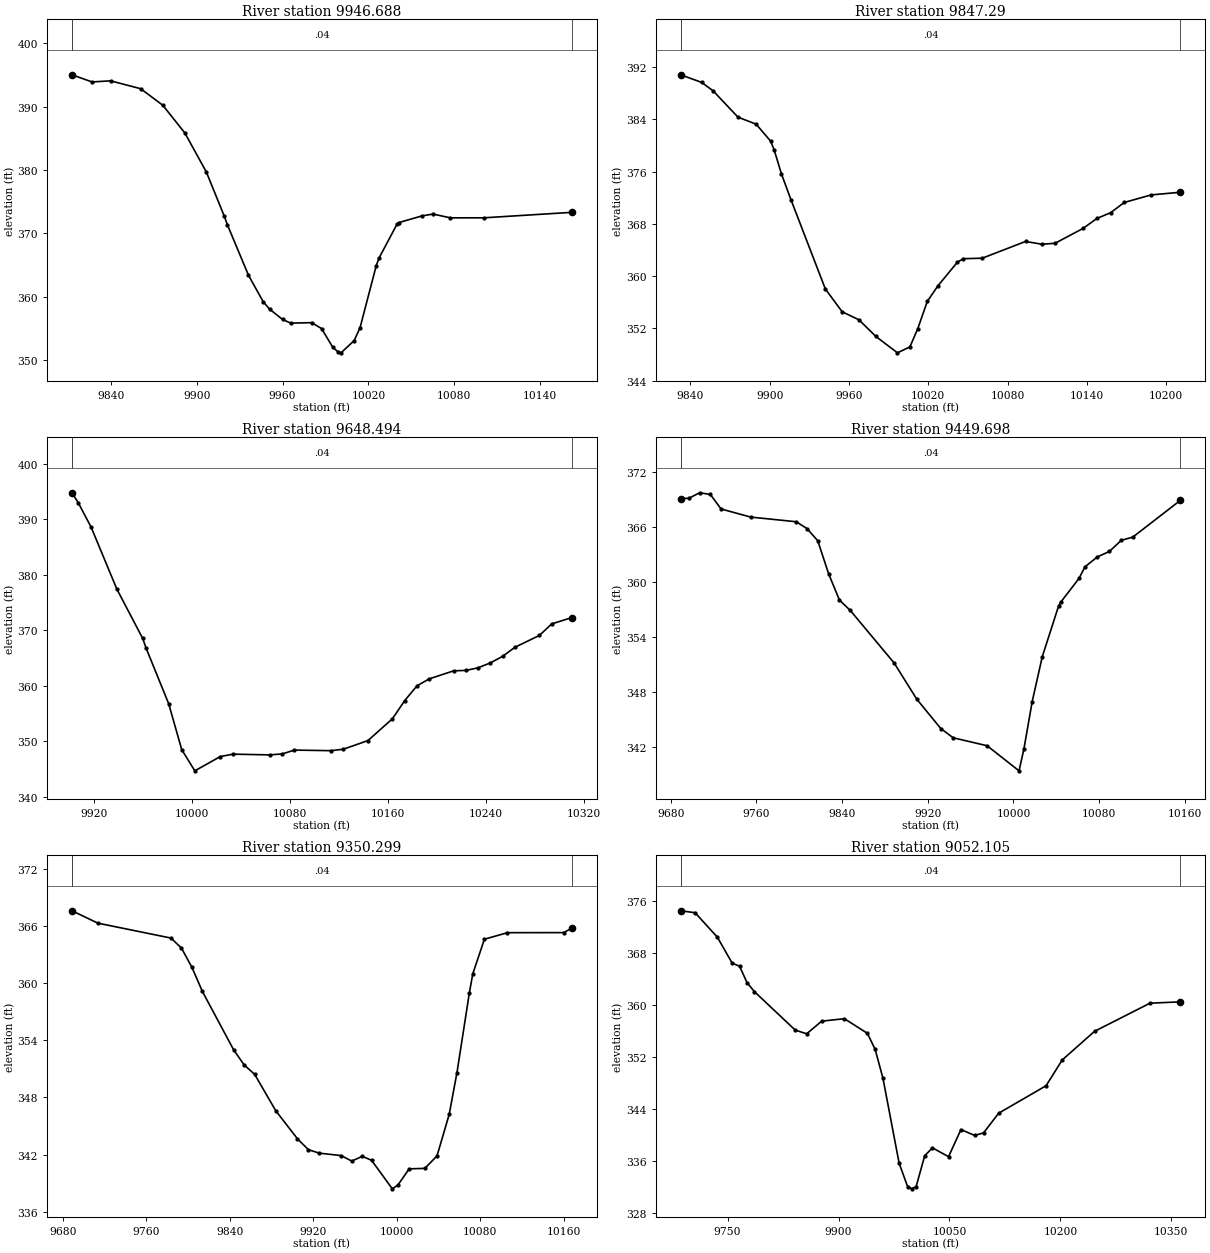
Type RM Length L Ch R = 1 ,9946.688,99.398000,99.398000,99.398000
XS GIS Cut Line= 6
781204.729101661801716.205369956781258.230256932801651.525922644
781328.979848353801574.911221279781363.480359906801533.471829977
781382.187411927801506.380327778781415.061676609801439.779076119
#Sta/Elev= 30
9812.753395.01319826.783393.88149839.731394.05839860.782392.8127 9876.25390.2064
9891.719385.81779906.692379.67669919.212372.71539921.431371.33359936.169363.3733
9946.438 359.1919950.907358.02089960.051356.37879965.645355.80869980.383355.8784
9987.277354.94879995.121351.9944    9999351.225210000.88351.114810010.11353.0519
10014.21355.093610025.42364.791310027.32366.024410040.15371.467910041.39371.6866
10057.61372.740310065.23373.022110077.38372.427710100.77372.432110162.24373.2944
#Mann= 3 , 0 , 0
9812.753    0.04       09812.753    0.04       010162.24    0.04       0
#XS Ineff= 2 , 0
       0                               0
Bank Sta=9812.753,10162.24
Exp/Cntr=0.3,0.1

Type RM Length L Ch R = 1 , 9847.29,198.796100,198.796100,198.796100
XS GIS Cut Line= 6
781263.990726485801762.380341777781318.923028389801709.430080374
781434.652132121801612.035345414781451.210954576801590.066406211
781468.687299944801553.819302907781486.688362821801473.153517719
#Sta/Elev= 30
9832.573390.8431 9848.44389.67849857.152388.38669875.973384.3537 9889.74383.2708
9900.803380.65269903.506379.24629908.907375.64389916.063371.71429942.111 358.028
9954.844354.53159967.577353.2959 9980.31350.7581 9996.73348.239110006.13349.1566
10012.12351.967710019.32356.137310027.46 358.541 10042.1362.135610046.58362.6637
 10060.9362.739510093.64365.304810106.07 364.878   10116 365.02810137.28367.3118
10147.66368.828510158.04  369.7110168.42371.282410188.74372.435910210.89372.8473
#Mann= 3 , 0 , 0
9832.573    0.04       09832.573    0.04       010210.89    0.04       0
#XS Ineff= 2 , 0
       0                               0
Bank Sta=9832.573,10210.89
Exp/Cntr=0.3,0.1

Type RM Length L Ch R = 1 ,9648.494,198.796000,198.796000,198.796000
XS GIS Cut Line= 6
781466.160270054801909.943422736781502.598915775801805.155692302
781509.048292664801763.565787485  781510.1551573 801730.65838851
781504.769438961801614.773008605781506.367498876 801508.60276163
#Sta/Elev= 30
9901.751394.7721 9906.94392.95439917.436 388.5559938.428377.40849959.534368.5258
9962.387366.74079980.788356.73949991.415 348.48710002.09344.668210022.98 347.246
10033.36347.675310063.48347.541810073.48347.717110083.49348.408210113.52348.3005
10123.53348.571910143.55350.122910163.57 354.06210173.58357.3322 10183.6  359.99
10193.61361.242210213.62362.693710223.62362.760910233.62363.244510243.62364.1282
10253.62365.308810263.62366.937910283.63369.071710293.63371.141710310.03372.2785
#Mann= 3 , 0 , 0
9901.751    0.04       09901.751    0.04       010310.03    0.04       0
#XS Ineff= 2 , 0
       0                               0
Bank Sta=9901.751,10310.03
Exp/Cntr=0.3,0.1

Type RM Length L Ch R = 1 ,9449.698,99.398100,99.398100,99.398100
XS GIS Cut Line= 6
781687.715930502801962.723970628781680.165233448801842.544247602
781663.178121538801754.721227746781642.778715283801713.776619806
781569.292458091801611.531943958781540.199659922801532.225634951
#Sta/Elev= 30
9689.202369.06449696.932369.1032 9706.94369.69839716.948369.51849726.957367.9338
 9754.65367.05149797.149366.54299807.189365.80159817.284364.46569827.397360.8741
9837.509358.01369847.622356.88389888.597351.15799909.777347.20859932.118344.0268
9943.658343.01789975.399342.149510005.19339.416410009.73341.789710017.49346.9601
10026.88351.838810042.11357.358410044.04 357.77110061.19360.370110066.72361.6289
10078.31362.716810089.52363.304610100.72364.522810111.42364.8701 10155.9368.8771
#Mann= 3 , 0 , 0
9689.202    0.04       09689.202    0.04       0 10155.9    0.04       0
#XS Ineff= 2 , 0
       0                               0
Bank Sta=9689.202,10155.9
Exp/Cntr=0.3,0.1

Type RM Length L Ch R = 1 ,9350.299,298.194000,298.194000,298.194000
XS GIS Cut Line= 6
  781699.3823049801939.893376494781694.992816332801777.578531819
781718.883491059801666.171518988781711.586151699801648.450226395
781670.272407514801588.581626951781626.858724228801487.602683919
#Sta/Elev= 30
9688.592367.63349713.508366.32959783.571364.7626 9793.58363.70699803.589361.6874
9813.592359.15579843.595 353.0079853.628351.42719863.756350.42839884.011346.5973
9904.732343.65849915.236342.51019925.741342.14299946.697341.88879956.806341.3095
9966.909341.81399975.841341.39049995.684338.3911   10001338.781110011.84340.4932
10026.92340.543110038.57341.859210050.22346.221610057.69350.619710069.59359.0182
10072.84361.001810083.99364.641210106.09365.330910159.91365.338110167.73365.7913
#Mann= 3 , 0 , 0
9688.592    0.04       09688.592    0.04       010167.73    0.04       0
#XS Ineff= 2 , 0
       0                               0
Bank Sta=9688.592,10167.73
Exp/Cntr=0.3,0.1

Type RM Length L Ch R = 1 ,9052.105,298.194100,298.194100,298.194100
XS GIS Cut Line= 6
781898.685496581802034.547706755781876.277268024801831.693176785
781828.025356957801703.494510334781860.609167344801644.865144948
 781863.07582438801614.791463971781775.475219442801396.318096712
#Sta/Elev= 30
9686.499374.45469706.093374.15699736.164370.39379756.211366.40869766.235365.9238
9776.259363.41949786.282362.02359841.476356.1079 9856.95355.54239877.278357.4823
9907.985 357.8649939.079 355.6119949.596353.13259960.114348.70149981.995335.6409
9993.399332.0603    9999 331.70310004.97332.044910016.55336.787510027.02338.0047
10048.83336.6494 10065.6340.820610084.05339.917910096.12340.303910116.57343.3281
 10180.7347.557510202.54351.517710246.22355.920210321.24360.247210362.39360.4507
#Mann= 3 , 0 , 0
9686.499    0.04       09686.499    0.04       010362.39    0.04       0
#XS Ineff= 2 , 0
       0                               0
Bank Sta=9686.499,10362.39
Exp/Cntr=0.3,0.1

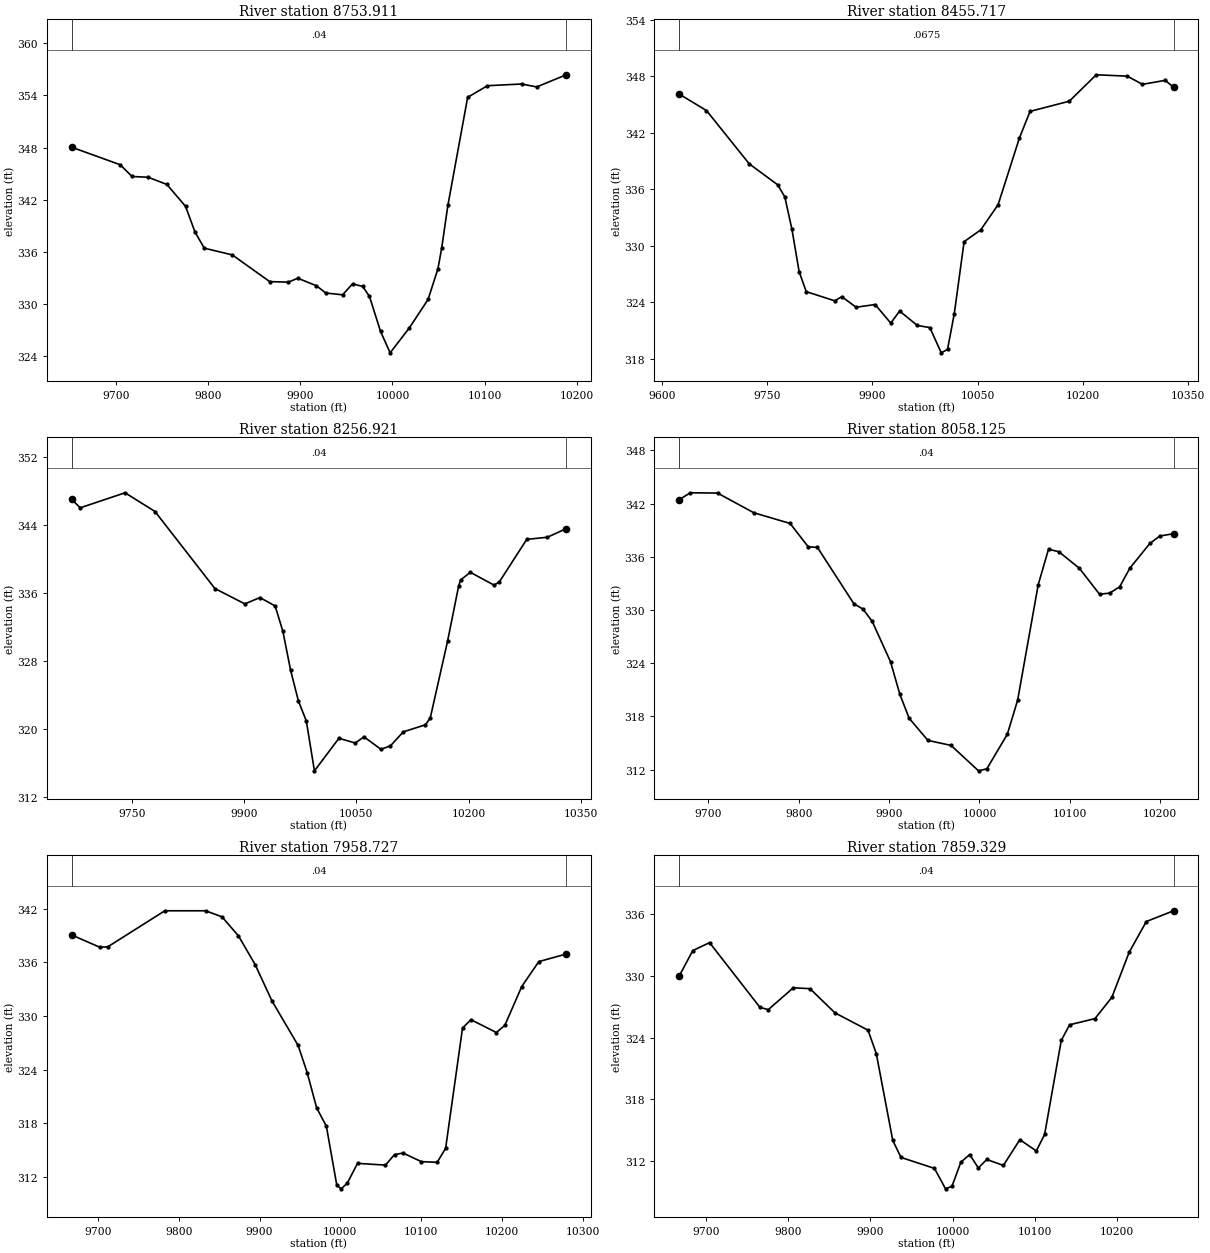
Type RM Length L Ch R = 1 ,8753.911,298.194100,298.194100,298.194100
XS GIS Cut Line= 6
782035.406996638801846.854458123781991.535859249801574.787778037
 781954.10928595801558.675723352781943.700742217 801548.49364117
781930.082076713801494.311198576781878.514572169801354.548408794
#Sta/Elev= 30
9652.319348.03629704.843346.02369717.691344.67089735.231344.58089755.489343.7546
9775.747341.22989785.876338.29939796.006336.42369826.393335.6476 9866.91 332.577
9887.168 332.5139897.297332.96769917.556332.10119927.685331.26629945.903331.0573
 9956.79332.31999967.677332.02119975.055330.87199987.047326.85049997.448324.3813
10018.08 327.22310038.58330.522510049.29 334.06210053.29336.405810060.02341.3327
10081.48 353.77810102.95355.112710139.89355.309810156.28354.972310188.32356.3707
#Mann= 3 , 0 , 0
9652.319    0.04       09652.319    0.04       010188.32    0.04       0
#XS Ineff= 2 , 0
       0                               0
Bank Sta=9652.319,10188.32
Exp/Cntr=0.3,0.1

Type RM Length L Ch R = 1 ,8455.717,198.796100,198.796100,198.796100
XS GIS Cut Line= 6
 782047.07417053801823.520110309782090.826072693801571.217474401
782152.394322306801490.788078353782254.422887534801418.012544706
782310.504941642801331.475029469 782357.26581189 801223.84346278
#Sta/Elev= 30
 9624.52346.09799663.615344.3369 9724.51 338.6779765.107336.44749775.256335.1568
9785.406331.70829795.555327.24199805.704325.10539846.301324.1279 9856.45324.5698
9876.749323.44769903.906323.73439926.198321.75939938.792323.04229963.979321.5117
9981.877321.28719998.109318.603310007.08318.9677 10016.7322.760310030.69330.4128
10054.37331.662210079.15334.341510109.48341.415110124.65344.249310180.64345.3318
10218.96348.137310263.23347.991810284.81347.120610317.16347.545210329.19346.8147
#Mann= 3 , 0 , 0
 9624.52  0.0675       0 9624.52  0.0675       010329.19  0.0675       0
#XS Ineff= 2 , 0
       0                               0
Bank Sta=9624.52,10329.19
Exp/Cntr=0.3,0.1

Type RM Length L Ch R = 1 ,8256.921,198.796000,198.796000,198.796000
XS GIS Cut Line= 6
782148.520807056801986.322071738782145.057445645 801772.11852473
 782161.27805418801681.400386432782204.724543492801587.324544045
782304.044716015801471.941916354782358.289163254801390.125819122
#Sta/Elev= 30
 9669.53347.00449680.855346.00779740.872347.78029780.883345.57299860.899336.5023
9900.993334.69579921.102335.43989941.468334.44799951.807331.44699962.146326.8596
9972.485323.27859983.131 320.8989993.951315.033810026.68318.8661 10048.5318.3117
10060.15319.0378 10082.9317.5662 10095.6317.982110112.76 319.62710142.34320.4551
10148.76321.264310171.93330.322210186.72 336.80710189.38337.522110202.36338.4138
 10233.9336.912410240.83337.251910277.74342.294110305.22342.542710330.49343.5549
#Mann= 3 , 0 , 0
 9669.53    0.04       0 9669.53    0.04       010330.49    0.04       0
#XS Ineff= 2 , 0
       0                               0
Bank Sta=9669.53,10330.49
Exp/Cntr=0.3,0.1

Type RM Length L Ch R = 1 ,8058.125,99.398100,99.398100,99.398100
XS GIS Cut Line= 6
782288.679078032801957.395409708782307.148520914801775.520603888
782325.414231457801688.094584809  782352.7145778801623.571171896
782400.511432521801535.765536862782446.214078554801441.037323241
#Sta/Elev= 30
9667.452342.4292  9679.9 343.2169710.027343.18429750.197340.96449790.375339.7575
9810.517337.11779820.588337.05959860.942330.7097 9871.08330.09499881.217328.7231
9901.562324.1626 9911.89320.48439922.217317.77919942.986315.28849968.553 314.724
    9999311.856610008.19312.085910030.92315.9903 10042.3319.838110065.07332.8497
10076.46336.844810087.84336.5718 10110.6334.704410132.95331.778510144.13331.8974
10155.31332.618410166.49334.709610188.68337.501410199.64338.335610214.94338.6027
#Mann= 3 , 0 , 0
9667.452    0.04       09667.452    0.04       010214.94    0.04       0
#XS Ineff= 2 , 0
       0                               0
Bank Sta=9667.452,10214.94
Exp/Cntr=0.3,0.1

Type RM Length L Ch R = 1 ,7958.727,99.398000,99.398000,99.398000
XS GIS Cut Line= 6
782336.840482703802019.202897542 782359.90940902801851.128002427
782376.983808231801776.808990531782396.575929503801731.824909492
782453.621924581801645.883742596782519.745906534 801442.86420096
#Sta/Elev= 30
9667.475339.06099701.999337.69829712.092337.73419782.749341.76489833.217341.7647
 9853.55341.08899873.916338.96359894.599335.74699915.364331.70199947.791 326.716
9959.004323.68289970.753319.73179982.751317.69319995.616311.1303   10001310.6958
 10008.6311.326110021.36313.543110055.93 313.34610067.11314.521310077.71314.6916
10100.39313.733510119.91313.660810130.38315.219810151.33328.6683 10161.8329.5947
10193.22328.1621 10203.7328.963510224.64333.303710245.76336.086310279.71336.9324
#Mann= 3 , 0 , 0
9667.475    0.04       09667.475    0.04       010279.71    0.04       0
#XS Ineff= 2 , 0
       0                               0
Bank Sta=9667.475,10279.71
Exp/Cntr=0.3,0.1

Type RM Length L Ch R = 1 ,7859.329,99.398000,99.398000,99.398000
XS GIS Cut Line= 6
782483.002625302802031.314099394782526.820251434801781.503242248
 782523.10160302 801736.94573386782496.454170484801656.961017934
782496.546506538801603.430182623782538.270643045801443.324442863
#Sta/Elev= 30
9666.859329.93969683.559332.43139704.034 333.2049765.361326.93489775.539326.7091
9806.075328.82779826.385328.74079856.759326.39819897.107324.71499907.151322.4471
9927.211314.03619937.214312.38589977.999311.32429991.517309.34079999.373309.5925
10010.16311.921510020.92312.661410031.44311.366910041.73312.1853   10062311.6091
10082.05314.104710102.09313.012810112.22314.610810132.51323.722410142.66325.2415
10173.57325.838110194.22327.911210215.19332.262410236.15335.249810269.35336.2904
#Mann= 3 , 0 , 0
9666.859    0.04       09666.859    0.04       010269.35    0.04       0
#XS Ineff= 2 , 0
       0                               0
Bank Sta=9666.859,10269.35
Exp/Cntr=0.3,0.1

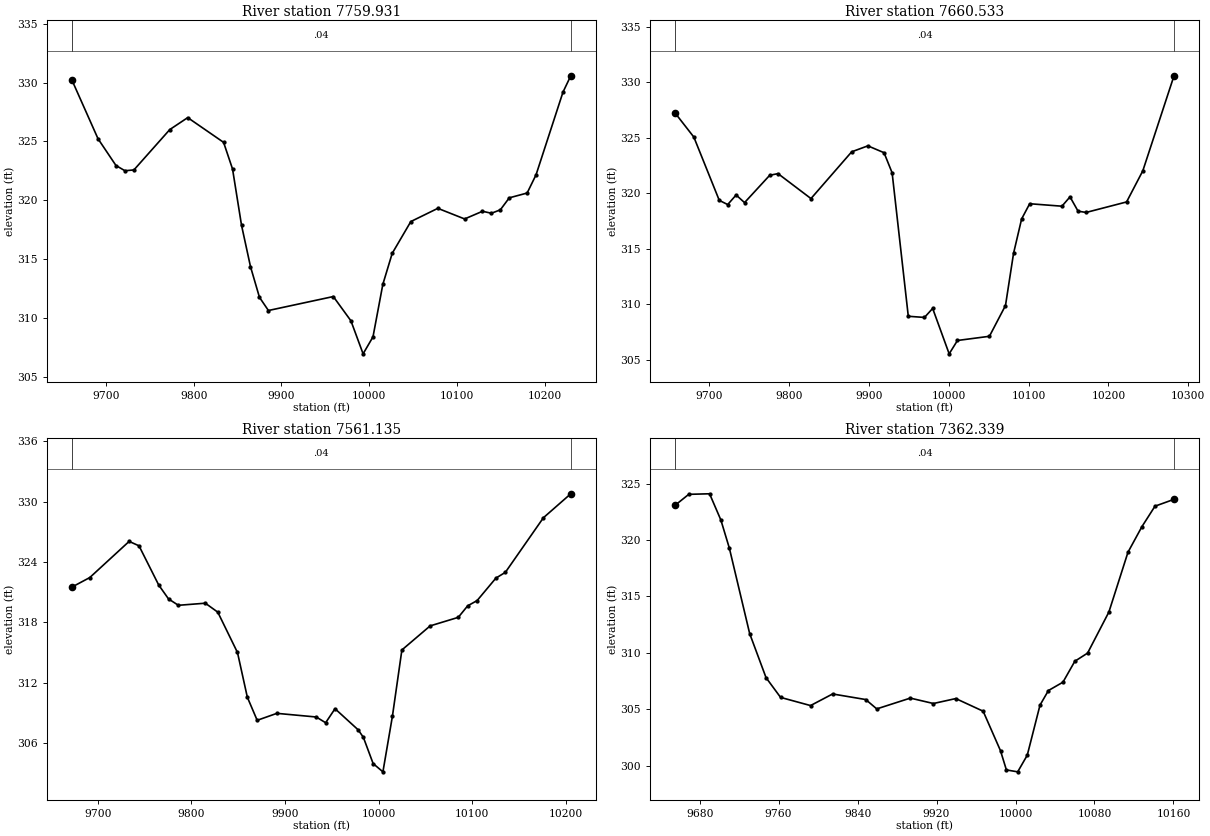
Type RM Length L Ch R = 1 ,7759.931,99.398100,99.398100,99.398100
XS GIS Cut Line= 6
782515.824398255 802004.13188272782565.428574126801770.500556862
782581.312176397801723.079037694782611.410948033801665.981888239
782621.656083883801638.977824387782659.074470464801456.382666659
#Sta/Elev= 30
9661.219330.2078    9691325.22439711.446 322.9569721.669322.51259731.892322.5806
9772.783 326.0079793.229327.02139834.121324.92219844.344322.65519854.566317.8873
9864.789314.37689875.012311.77189885.235310.65059959.214311.83569979.279309.7782
9993.173306.973210004.45308.414310015.66312.866510026.36315.502610047.58318.1997
10078.38319.322110108.92318.421210129.28 319.07210139.46318.904210149.64319.1961
10159.82320.213410180.18320.621410190.36322.170910221.06329.187410229.93330.5721
#Mann= 3 , 0 , 0
9661.219    0.04       09661.219    0.04       010229.93    0.04       0
#XS Ineff= 2 , 0
       0                               0
Bank Sta=9661.219,10229.93
Exp/Cntr=0.3,0.1

Type RM Length L Ch R = 1 ,7660.533,99.398000,99.398000,99.398000
XS GIS Cut Line= 6
782577.478964827802087.358863641782613.179658295  801982.0213171
782634.580806336801897.482155824782663.498137255801745.141222632
782663.619922493801696.980275125782700.224947618801476.789255737
#Sta/Elev= 30
9657.013327.23419680.445325.07079712.298319.36839722.856318.98939733.415319.8528
9743.974319.16529775.528321.62959785.913321.77799827.224319.52929878.252323.7445
9898.522324.28139918.792323.66359928.927321.85269949.198308.91979969.468308.8155
9979.733309.627510000.42305.534110010.82306.738210050.87 307.11610071.01309.8897
10081.12 314.59610091.22317.692410101.33319.064310141.75318.841710151.86319.6837
10161.97 318.39310172.07318.279110222.77319.225610243.13322.034310282.21330.5976
#Mann= 3 , 0 , 0
9657.013    0.04       09657.013    0.04       010282.21    0.04       0
#XS Ineff= 2 , 0
       0                               0
Bank Sta=9657.013,10282.21
Exp/Cntr=0.3,0.1

Type RM Length L Ch R = 1 ,7561.135,198.796100,198.796100,198.796100
XS GIS Cut Line= 6
782650.850420624802013.111686409782731.705179244801765.000000015
782734.017357787801720.349745442782721.026290304801660.146115501
782720.350952514801626.369330814782739.762859688801496.396171146
#Sta/Elev= 30
9672.546321.50529691.595 322.4529733.665 326.0539744.183325.61219765.218321.7132
9775.735320.32369786.253319.69179815.036319.90049828.323319.00849849.359314.9932
9859.876310.54519870.394308.24289891.429308.93579933.499308.57249943.513308.0006
9953.526309.39589978.209307.29789983.796306.55149994.239303.934310004.68303.1135
10014.83  308.6510024.94315.244410055.11317.640410085.16318.492210095.21319.6389
10105.26320.159710125.35322.398610135.45322.971510176.09328.407610205.31330.7926
#Mann= 3 , 0 , 0
9672.546    0.04       09672.546    0.04       010205.31    0.04       0
#XS Ineff= 2 , 0
       0                               0
Bank Sta=9672.546,10205.31
Exp/Cntr=0.3,0.1

Type RM Length L Ch R = 1 ,7362.339,99.398000,99.398000,99.398000
XS GIS Cut Line= 6
782708.308469617802025.469512275782837.290661029801786.086515746
782863.569274913801758.410706603782943.777923283801711.497943298
782971.729265417801688.681486978783016.309834354 801640.16999523
#Sta/Elev= 30
9655.212323.08989668.979324.05679690.077324.1057 9701.52321.78049710.126 319.283
  9730.7311.7111 9747.29307.80199761.993306.05479792.352305.32929814.715306.3583
 9848.26305.86329859.441305.03419893.428 305.9919916.827305.51229939.498305.9503
9967.222304.82879984.796301.32619990.759299.623210002.21299.4541 10011.9300.9285
10024.82305.370910033.34306.662610048.06307.4023 10060.1309.259210073.01 309.981
 10094.6313.624510113.94318.925810128.08321.194510141.29323.005810160.56323.6133
#Mann= 3 , 0 , 0
9655.212    0.04       09655.212    0.04       010160.56    0.04       0
#XS Ineff= 2 , 0
       0                               0
Bank Sta=9655.212,10160.56
Exp/Cntr=0.3,0.1