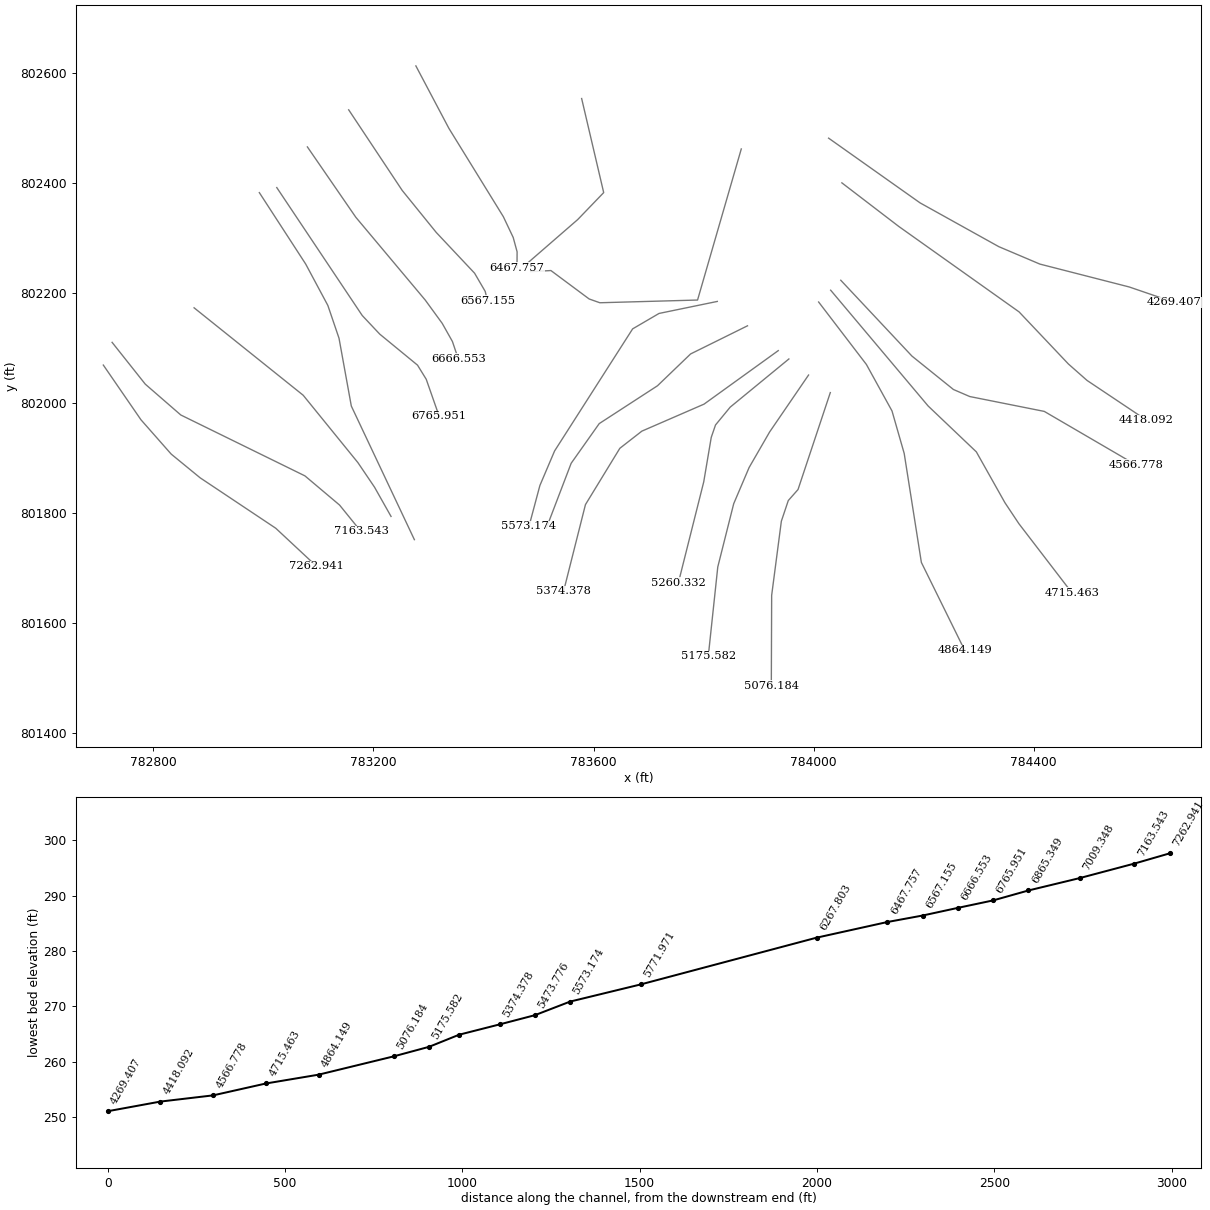
HEC-RAS study 17672_ras.prj: 17672

--- 17672_ras.g01 (geometry) --- (continued)

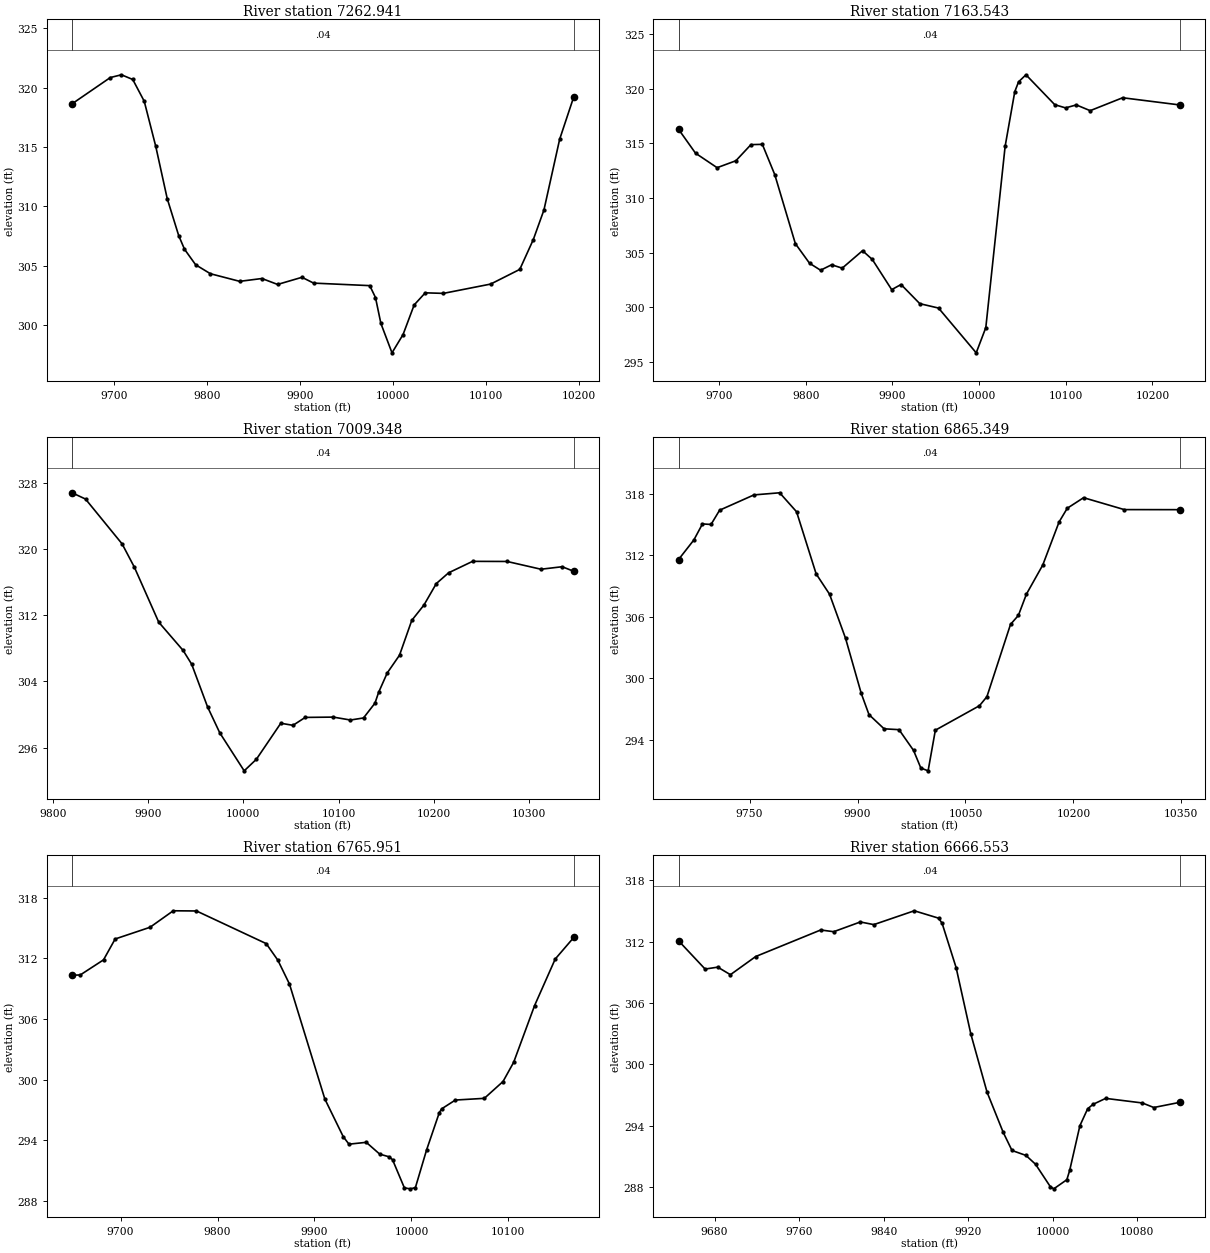
Type RM Length L Ch R = 1 ,7262.941,99.398000,99.398000,99.398000
XS GIS Cut Line= 6
 782709.00574951802069.451693012782777.437001853801969.979410634
782832.389556998801907.616978297782885.017845976801864.484765884
783022.398342122801772.880043461783096.751882077801703.531882142
#Sta/Elev= 30
9655.167 318.6489696.275320.86269708.208321.09499720.352320.6984  9732.7318.8631
9745.048  315.079757.395310.65599769.743307.53719775.942306.39399787.933 305.082
9803.788304.32839835.265303.68619859.114303.92539875.963303.42549902.137304.0271
9914.663303.5377 9974.97303.32529981.122302.32339986.915300.1438 9998.86297.6613
10010.76299.203610022.68301.6989 10034.6302.719410054.05302.672210104.86303.4567
10136.14304.693210150.69307.2099 10162.1309.700410178.97315.658910194.24319.2624
#Mann= 3 , 0 , 0
9655.167    0.04       09655.167    0.04       010194.24    0.04       0
#XS Ineff= 2 , 0
       0                               0
Bank Sta=9655.167,10194.24
Exp/Cntr=0.3,0.1

Type RM Length L Ch R = 1 ,7163.543,154.194700,154.194700,154.194700
XS GIS Cut Line= 6
782724.965282355802110.733267232782785.244550577802034.777451579
782849.792081311801978.736691473783075.476361543801868.039296066
783138.365860683801815.047284745 783177.33825395801767.007449035
#Sta/Elev= 30
9653.374316.27889672.957314.0906 9697.85312.76279719.498313.39719736.885314.8726
9750.038314.89879764.367312.12749788.114 305.811 9804.47304.01749817.196303.3782
9829.921303.87779842.165303.56799865.618 305.1679876.879304.36189899.222301.6013
9910.028302.07119931.639 300.3189953.251299.91549996.714295.817210007.79298.1291
10030.07314.7195 10041.2319.721610045.58320.620710054.09 321.266 10087.3318.5282
10099.73318.236310112.21318.507410128.15317.9813 10165.6319.163410232.14318.4984
#Mann= 3 , 0 , 0
9653.374    0.04       09653.374    0.04       010232.14    0.04       0
#XS Ineff= 2 , 0
       0                               0
Bank Sta=9653.374,10232.14
Exp/Cntr=0.3,0.1

Type RM Length L Ch R = 1 ,7009.348,143.999400,143.999400,143.999400
XS GIS Cut Line= 5
782873.985121727802173.535327718783072.327078253802014.570083141
783171.749764282801892.148065956 783201.93068054801847.543622277
783231.978423182801794.312701104
#Sta/Elev= 30
9820.162326.77449834.278326.01649872.724320.5972 9885.54 317.7969911.171 311.146
9936.801307.72949945.739306.07299962.432300.91669975.248297.785710000.88293.1951
10013.69294.592710039.32298.941410052.14 298.69210064.96299.646910094.45299.6848
10112.44 299.33210126.17299.5814 10138.2301.368610142.04 302.67210151.09 305.016
10163.97307.158910176.85311.364210189.62313.215210202.62315.8106 10215.5317.1085
10240.69318.493510276.91318.4797 10312.5317.541610334.76317.843810347.04317.2883
#Mann= 3 , 0 , 0
9820.162    0.04       09820.162    0.04       010347.04    0.04       0
#XS Ineff= 2 , 0
       0                               0
Bank Sta=9820.162,10347.04
Exp/Cntr=0.3,0.1

Type RM Length L Ch R = 1 ,6865.349,99.398000,99.398000,99.398000
XS GIS Cut Line= 6
782992.595282241802382.892533334783076.838959395802253.084345818
  783117.1124149802177.856822415 783137.42387813802118.198054449
783159.779314102801994.961159682783274.398887282801752.111018123
#Sta/Elev= 30
9651.236311.59079672.567313.50429684.488315.06749696.409315.01549708.331316.4067
9756.016317.8988 9791.78318.10759815.301 316.254 9842.53310.18769861.127308.2087
9883.402303.89839905.198298.52539915.962296.45219936.968295.06739957.689294.9839
9977.912292.95629988.023291.24119998.134290.964510008.21294.931710069.53297.3214
10079.87298.203110112.68305.259110123.62306.1369 10134.8308.213210157.51311.0547
10180.21315.261510191.56316.596710214.26 317.62910270.79316.465210348.72 316.459
#Mann= 3 , 0 , 0
9651.236    0.04       09651.236    0.04       010348.72    0.04       0
#XS Ineff= 2 , 0
       0                               0
Bank Sta=9651.236,10348.72
Exp/Cntr=0.3,0.1

Type RM Length L Ch R = 1 ,6765.951,99.398100,99.398100,99.398100
XS GIS Cut Line= 6
783024.295542428802392.074909454783179.644131894802159.495541543
783211.425052551802125.726398977783280.145928547802069.292317929
783295.961136711802043.620070012783319.504399514801976.347878419
#Sta/Elev= 30
9649.989310.32819658.469310.3582 9682.44311.85269694.426  313.929730.383315.0781
9754.354316.71339778.325 316.6949850.239 313.4619862.225311.8194 9874.21309.4564
9910.699298.06919929.698294.33419935.596 293.5959953.418293.77799967.303292.6088
9977.376292.33389980.558292.04869992.757289.2614    9999289.1711 10004.1289.2937
 10015.7293.042910028.76296.718810031.19297.095610045.33297.9661 10075.2298.1349
10094.48299.801810105.42301.697910127.06307.3306 10148.3311.931510167.54314.0822
#Mann= 3 , 0 , 0
9649.989    0.04       09649.989    0.04       010167.54    0.04       0
#XS Ineff= 2 , 0
       0                               0
Bank Sta=9649.989,10167.54
Exp/Cntr=0.3,0.1

Type RM Length L Ch R = 1 ,6666.553,99.398000,99.398000,99.398000
XS GIS Cut Line= 6
783079.932551543802465.990231647783167.914990251802338.180484225
783294.126512039802187.637080053783325.031076406802145.236031267
783343.561893547802112.294059282783354.048847872802081.211466202
#Sta/Elev= 30
9645.871 312.0769671.007309.30989682.982309.49639694.957308.75839718.908310.5367
9780.379313.12979792.678312.96219817.881313.91389830.638313.65519868.912315.0075
9891.916314.28559895.252313.78169908.476309.46049922.481302.93619937.763297.2771
9953.046293.34559961.373 291.5729974.597291.0885 9983.61290.22899997.558288.0456
10000.89287.822110013.25288.712910015.93 289.61610025.61293.997110032.95295.6492
10037.96296.077710049.97 296.66610084.72296.217510095.52 295.77410120.63 296.289
#Mann= 3 , 0 , 0
9645.871    0.04       09645.871    0.04       010120.63    0.04       0
#XS Ineff= 2 , 0
       0                               0
Bank Sta=9645.871,10120.63
Exp/Cntr=0.3,0.1

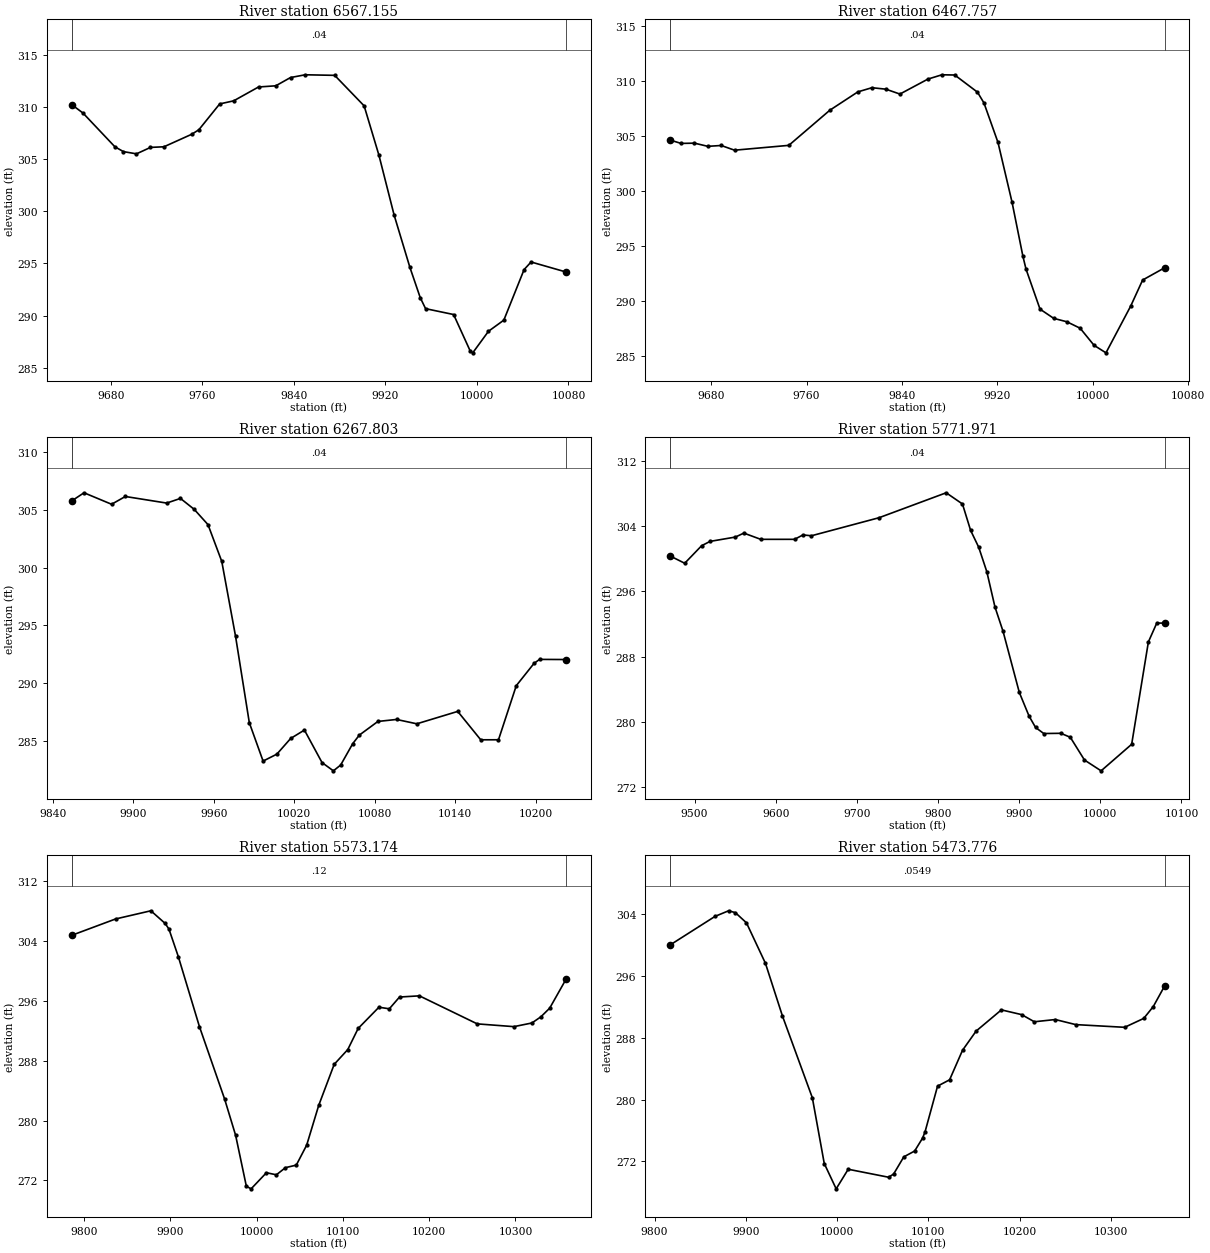
Type RM Length L Ch R = 1 ,6567.155,99.398000,99.398000,99.398000
XS GIS Cut Line= 6
783155.008975262802533.397994566783252.266570641802386.911802137
783314.165405998802310.508791894783383.818915315802236.474505582
783403.156105691802203.348739199783407.206648339802186.052271513
#Sta/Elev= 30
9645.901310.22249655.802309.41069683.647306.18189691.169305.71679702.528305.5058
9714.748306.12289726.537306.18269750.776307.38139757.037307.8137 9775.23310.2881
9787.457310.58459809.172311.91129824.261312.02519837.131312.81689850.001313.0815
9875.741 313.0279901.481310.10269914.351305.3971  9927.7299.6343 9941.44294.6407
9950.512291.7257 9955.18290.67079979.675290.10899994.257286.5978  9996.4286.4377
10010.16288.504710023.58289.571710041.28294.417210047.39295.142410078.04294.1798
#Mann= 3 , 0 , 0
9645.901    0.04       09645.901    0.04       010078.04    0.04       0
#XS Ineff= 2 , 0
       0                               0
Bank Sta=9645.901,10078.04
Exp/Cntr=0.3,0.1

Type RM Length L Ch R = 1 ,6467.757,199.954100,199.954100,199.954100
XS GIS Cut Line= 6
783277.137184321802613.218153224 783337.16278326 802499.68009623
783436.093844227802339.205469373783454.040076913802301.398723204
783461.124415395802275.338299557783460.930701223802246.773039812
#Sta/Elev= 30
9645.578304.60859654.789304.30319665.998304.32649677.207304.03779688.415304.1147
9699.624303.68669745.109 304.1269779.525307.3217 9803.02308.98889814.768 309.367
9826.515309.23339838.263308.78929861.758310.15059873.506310.54239884.239310.5209
9903.295308.96129908.749307.97669920.496304.39289932.244 298.9779941.406294.0336
9943.991292.87899955.739289.23849967.212288.40049978.307288.08749989.402287.5007
   10001285.953610011.03285.265210031.75 289.51210041.77291.883710060.15292.9936
#Mann= 3 , 0 , 0
9645.578    0.04       09645.578    0.04       010060.15    0.04       0
#XS Ineff= 2 , 0
       0                               0
Bank Sta=9645.578,10060.15
Exp/Cntr=0.3,0.1

Type RM Length L Ch R = 1 ,6267.803,495.832100,495.832100,495.832100
XS GIS Cut Line= 4
783578.438340127802553.945708901783618.518754035802382.935942993
783571.312933236802333.948770478783476.901291639802252.006590977
#Sta/Elev= 30
9854.076 305.7639863.264306.46699883.806305.47449894.077 306.146 9924.89305.5765
9935.161305.97999945.432305.03349955.703303.71239965.974300.53229976.245294.0645
9986.515286.58879996.786283.271410007.06283.872610017.33285.2263 10027.6 285.953
10040.74283.1413 10049.2282.428310054.63 282.93110063.61284.775210068.52285.5156
 10082.4286.698810096.29286.8702 10111.4286.494110141.91287.566610159.07285.1114
10172.31285.113910185.56289.7895 10198.8291.718410202.94292.062810222.76292.0508
#Mann= 3 , 0 , 0
9854.076    0.04       09854.076    0.04       010222.76    0.04       0
#XS Ineff= 2 , 0
       0                10096.02       0
Bank Sta=9854.076,10222.76
Exp/Cntr=0.3,0.1

Type RM Length L Ch R = 1 ,5771.971,198.796100,198.796100,198.796100
XS GIS Cut Line= 6
783868.611697912 802462.29788211783789.138010889802187.656146616
783611.542949587802182.716926515783592.095209241802189.588160113
783522.577689767802241.272429764783485.787045658802239.240043342
#Sta/Elev= 30
9469.889300.35149487.897299.45489508.717301.60759519.128302.13889550.359302.6711
9560.769303.15729581.589302.3913 9623.23 302.3939633.641302.93239644.051302.8293
9727.333305.04279810.099 308.105 9830.16306.7282 9840.19303.49499850.209301.4158
9860.209298.40559870.209294.0899 9880.21 291.0919900.211283.60439912.247280.6934
9920.273279.3007 9930.35278.56029951.379 278.5889963.053278.0994  9980.5275.3085
   10001 273.98110038.66277.239910059.27289.802910069.63292.119910079.19292.1082
#Mann= 3 , 0 , 0
9469.889    0.04       09469.889    0.04       010079.19    0.04       0
#XS Ineff= 2 , 0
       0                               0
Bank Sta=9469.889,10079.19
Exp/Cntr=0.3,0.1

Type RM Length L Ch R = 1 ,5573.174,99.398000,99.398000,99.398000
XS GIS Cut Line= 6
783825.009824891 802185.12177086783719.103944482802163.284838519
783671.123492253802135.241596599 783529.24781407801913.315895344
 783502.53896643801850.534685277783482.734024186801776.392475947
#Sta/Elev= 30
9785.803304.73589836.631  306.929877.562308.01429894.009 306.3339898.473305.5786
 9909.35 301.8949933.819292.5482 9963.06282.85499975.778278.02569988.206271.2269
9993.702270.881610011.46273.0339   10023272.755810033.54273.713110046.07274.0487
10058.12276.721110072.04282.0215   10090287.506810105.73289.481210117.77292.3026
10141.84295.135510153.88294.923910165.71296.496510188.76296.654210255.78292.9109
10298.25292.541510319.15293.030910329.48 293.85110339.73295.009610358.81298.9057
#Mann= 3 , 0 , 0
9785.803    0.12       09785.803    0.12       010358.81    0.12       0
#XS Ineff= 2 , 0
       0                               0
Bank Sta=9785.803,10358.81
Exp/Cntr=0.3,0.1

Type RM Length L Ch R = 1 ,5473.776,99.398100,99.398100,99.398100
XS GIS Cut Line= 6
783879.927145557802140.823821585783776.495821153802089.681002689
783716.279906022802031.809607294783610.388249617801963.047365633
783559.409489491801890.972069026783514.389902359801773.191018719
#Sta/Elev= 30
9817.055300.04499866.355303.75599881.181304.47929888.587304.23619900.733302.9169
9921.488297.68349940.195290.82869972.935280.23199985.991271.70869999.043268.4234
10012.24270.963210056.53 269.92710062.01270.348410073.14272.568510085.04273.3271
10093.68274.993410096.39275.796410110.14281.740610123.34282.5623 10137.5286.3895
 10152.4288.8795 10180.1291.629210202.31291.0126 10216.2290.087510239.18290.3776
10261.57 289.71910315.15289.368610336.08290.523210346.54292.058910358.89294.7129
#Mann= 3 , 0 , 0
9817.055  0.0549       09817.055  0.0549       010358.89  0.0549       0
#XS Ineff= 2 , 0
       0                               0
Bank Sta=9817.055,10358.89
Exp/Cntr=0.3,0.1

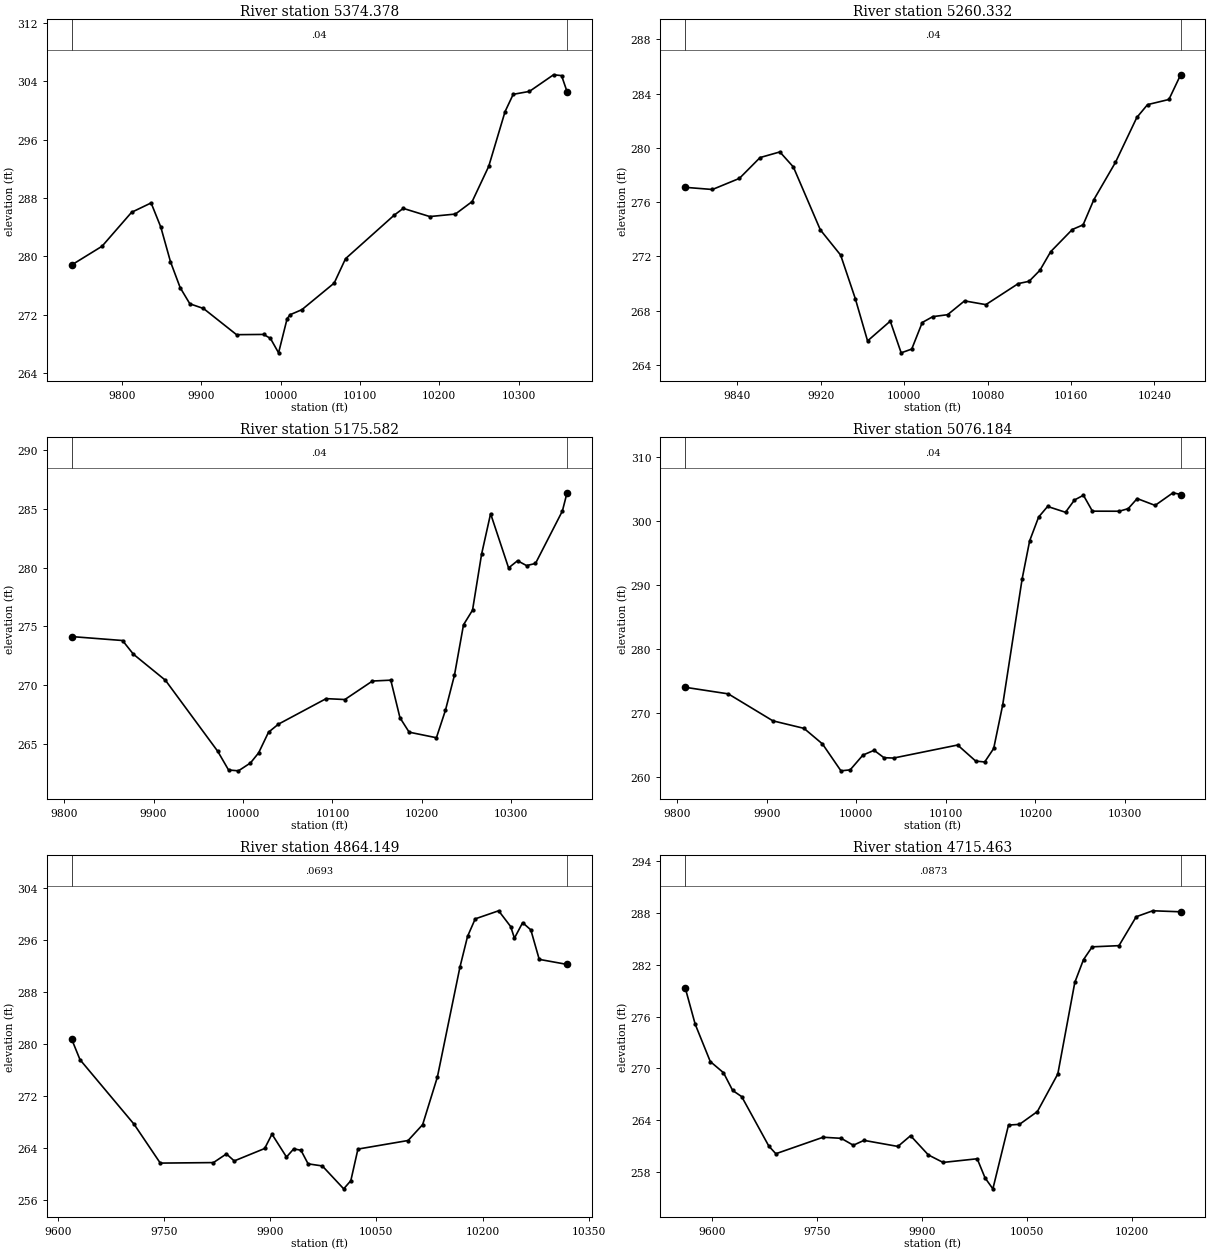
Type RM Length L Ch R = 1 ,5374.378,114.046500,114.046500,114.046500
XS GIS Cut Line= 6
783935.842750799802095.720626187783800.927973227801998.442800777
783687.888778853801949.351853472783647.865542177801918.154690564
783585.353446298801815.792456581783545.571613165 801658.15126378
#Sta/Elev= 30
9736.175 278.8059774.524281.37169811.825286.03029836.439287.31339848.659284.0069
9860.879279.25419873.099 275.6999885.319273.48249902.515 272.8399944.223269.2482
9978.375269.28259986.976268.73599997.243266.758110008.07271.466810012.13272.0007
10026.64272.676910067.39276.323710081.71279.6692 10143.1285.639810154.53 286.566
   10188285.444910220.29285.788110241.44287.5036 10262.3292.320210282.97299.8427
10293.21302.207610313.69302.6075 10344.1304.887210354.21304.774110361.14302.5793
#Mann= 3 , 0 , 0
9736.175    0.04       09736.175    0.04       010361.14    0.04       0
#XS Ineff= 2 , 0
       0                               0
Bank Sta=9736.175,10361.14
Exp/Cntr=0.3,0.1

Type RM Length L Ch R = 1 ,5260.332,84.749500,84.749500,84.749500
XS GIS Cut Line= 6
783955.140191944 802080.53343414783848.421128905801992.937612851
783821.778919631801960.563766987783814.014698964801938.012701718
783800.344605811801857.068152086783754.314204357801673.920143273
#Sta/Elev= 30
9790.059277.09579816.115276.93649841.989277.75419861.827279.29029880.801279.7049
9893.738278.59829919.613273.96139939.079272.10119953.137268.89229964.895265.7745
 9986.67267.23389997.114 264.89610007.25265.173710017.34267.132110027.43267.5641
10041.64 267.70710057.89268.725310078.34268.449110109.41269.999910119.77270.1686
10130.13270.976710140.49272.352110161.21273.987110171.57  274.3310181.93276.1952
10202.55278.927710223.08 282.24510233.35283.191110253.85283.5715 10265.1285.3919
#Mann= 3 , 0 , 0
9790.059    0.04       09790.059    0.04       0 10265.1    0.04       0
#XS Ineff= 2 , 0
       0                               0
Bank Sta=9790.059,10265.1
Exp/Cntr=0.3,0.1

Type RM Length L Ch R = 1 ,5175.582,99.398100,99.398100,99.398100
XS GIS Cut Line= 6
783990.883561485802051.323066178783920.140672371801947.864209029
783882.878446718801883.292014317783854.851702252801817.470892823
783825.898040883801702.493846993783808.569604114801539.796473147
#Sta/Elev= 30
9808.377274.13029865.272273.7952  9877.4272.63399913.255270.41269971.735264.3694
 9983.81262.78219994.861262.708610008.29263.377410017.44 264.23710028.48265.9918
10039.53266.677410092.93268.851710113.85268.7746 10144.7270.3486 10165.2270.4225
10175.45267.2255 10185.7265.998810216.19265.524510226.29267.860610236.39 270.851
10246.48275.132210256.58276.378110266.68281.134810276.78284.584910296.88279.9707
10306.91280.583510316.93280.169710326.96280.349910357.03284.811610362.24286.3632
#Mann= 3 , 0 , 0
9808.377    0.04       09808.377    0.04       010362.24    0.04       0
#XS Ineff= 2 , 0
       0                10108.44       0
Bank Sta=9808.377,10362.24
Exp/Cntr=0.3,0.1

Type RM Length L Ch R = 1 ,5076.184,212.035400,212.035400,212.035400
XS GIS Cut Line= 6
784030.436069683802019.418833041783971.764323685801843.236498636
783954.048630706801823.185278529783941.454849702801785.668765472
783923.827570962801650.940858729783923.214059741 801486.46817618
#Sta/Elev= 30
9808.927274.0478 9857.04 273.0199906.821268.80429941.541 267.6289962.182265.1947
9982.822260.98739993.142  261.1410007.39263.452210019.86 264.19610030.86263.0431
10041.59262.986210113.13265.023910133.31262.514310143.35 262.372 10153.4264.4831
10163.44271.277910185.18291.003710193.57296.948710203.59 300.661 10213.6302.3158
10233.61301.406710243.62303.327310253.62304.069710263.63301.580310293.64301.5702
10303.64301.979510313.64303.551210333.65302.481910353.65304.454910362.18304.1858
#Mann= 3 , 0 , 0
9808.927    0.04       09808.927    0.04       010362.18    0.04       0
#XS Ineff= 2 , 0
       0                10043.62       0
Bank Sta=9808.927,10362.18
Exp/Cntr=0.3,0.1

Type RM Length L Ch R = 1 ,4864.149,148.685600,148.685600,148.685600
XS GIS Cut Line= 6
784009.215733899802184.064715421784096.036917714802070.540245458
784142.585437355801986.037331814 784164.74885076801908.796756186
784195.954646828801710.726506543784274.780420977801550.798354829
#Sta/Elev= 30
 9619.58280.71279631.421277.53959707.861267.60069744.795261.63289819.889261.7119
9838.202263.04399849.251261.96719892.226263.87899902.546266.08329923.058262.5672
9933.314263.82679943.496263.60729953.559261.51999973.683261.194610003.86257.6742
10013.92258.926710023.97263.788810094.82265.109210115.36267.546410136.16274.8608
10167.93291.725810178.76296.493810189.62299.1984 10222.7300.442310239.71298.0129
10245.01296.227710256.59298.614410268.16297.503510280.04292.967710319.32292.1932
#Mann= 3 , 0 , 0
 9619.58  0.0693       0 9619.58  0.0693       010319.32  0.0693       0
#XS Ineff= 2 , 0
       0                               0
Bank Sta=9619.58,10319.32
Exp/Cntr=0.3,0.1

Type RM Length L Ch R = 1 ,4715.463,148.685500,148.685500,148.685500
XS GIS Cut Line= 6
784031.072594603802205.557295107784208.286634717801995.028264768
784295.879161909801911.680849542784347.838343823801819.273056229
784373.289460788801781.041596842784469.739594484801655.374156695
#Sta/Elev= 30
 9562.32279.32229576.529275.12059598.071270.79999616.905269.50969630.002267.4565
9642.908266.74119681.625261.01789691.605260.1391 9759.06262.04749784.872  261.92
9802.105261.12139817.333261.68449865.719260.98239883.795262.22449909.175259.9993
  9930.2259.13319978.873259.55699990.036257.346110001.22 256.07910023.51263.4521
10039.18263.5378 10064.7265.017510093.86269.368110118.11279.9603 10130.5282.5886
10142.88284.0654 10181.1284.203710205.69287.548910229.32288.236810269.08288.1191
#Mann= 3 , 0 , 0
 9562.32  0.0873       0 9562.32  0.0873       010269.08  0.0873       0
#XS Ineff= 2 , 0
       0                               0
Bank Sta=9562.32,10269.08
Exp/Cntr=0.3,0.1

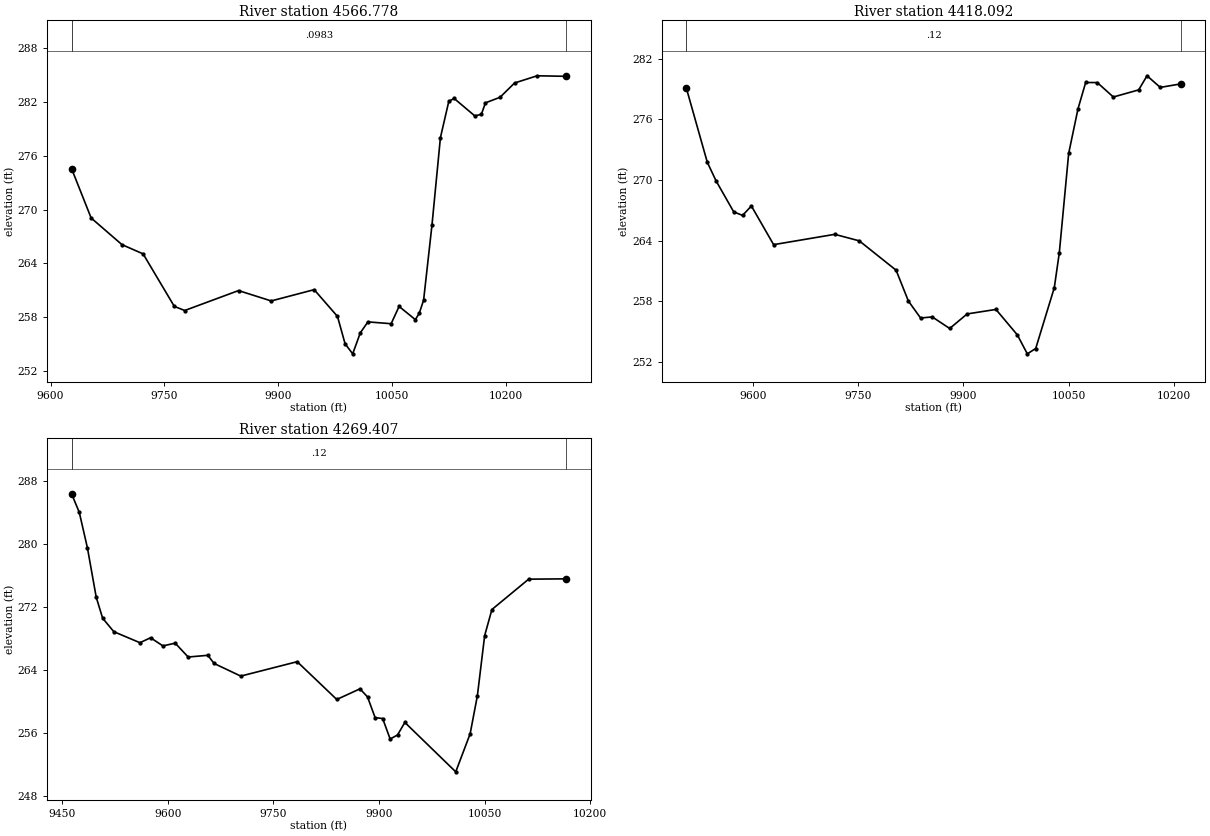
Type RM Length L Ch R = 1 ,4566.778,148.685600,148.685600,148.685600
XS GIS Cut Line= 6
 784049.45578223802223.634096268784178.840198846802085.772300079
784254.310636173802025.000764568784283.945587451802012.235259514
784419.370985586801985.236451704784586.465149996801887.775444379
#Sta/Elev= 30
9627.647274.55329653.413269.05999694.025 266.0929721.897265.06219762.987259.2177
9776.684258.7584 9847.58260.97789890.635259.82359947.218261.07949977.919258.1006
9987.953255.05259997.971253.934410007.98256.271710018.02257.491510048.62 257.289
10059.09259.213810080.48257.7421 10085.7258.456910091.38259.915710102.45268.3081
10113.52 278.00210124.58282.050510131.61282.365510158.75280.429210167.43280.5922
10172.85281.877310192.04282.496210211.24284.089510240.98284.891510278.87284.8309
#Mann= 3 , 0 , 0
9627.647  0.0983       09627.647  0.0983       010278.87  0.0983       0
#XS Ineff= 2 , 0
       0                               0
Bank Sta=9627.647,10278.87
Exp/Cntr=0.3,0.1

Type RM Length L Ch R = 1 ,4418.092,148.685500,148.685500,148.685500
XS GIS Cut Line= 6
784051.449912703802400.646020345784154.803504169802321.492510475
784373.564204799802166.090850938784463.228706318802071.404774747
784497.118097749802041.506698824784605.287959688801969.189765809
#Sta/Elev= 30
9505.202279.08119535.056  271.759547.629269.89969572.774266.83879585.347266.4949
9597.919267.42499629.603263.60229716.704264.62319751.683263.97849804.152261.0771
9821.642258.03119839.025256.35299855.663256.45979880.535255.31739905.375256.7558
9946.434257.19999976.959254.68139991.132252.8111 10003.1253.336310029.63259.3551
10036.77262.8175 10050.1272.625510063.44277.045310074.32279.629910090.86279.6213
10113.75278.196210149.85278.898810161.76280.293810180.63279.144510209.74279.4912
#Mann= 3 , 0 , 0
9505.202    0.12       09505.202    0.12       010209.74    0.12       0
#XS Ineff= 2 , 0
       0                               0
Bank Sta=9505.202,10209.74
Exp/Cntr=0.3,0.1

Type RM Length L Ch R = 1 ,4269.407,0.000000,0.000000,0.000000
XS GIS Cut Line= 6
784027.344399569802481.916036034784193.556300504802364.277597367
784336.708615755802284.680583648784411.343658183802253.014992059
784573.816456621802211.393080074784654.873724772802183.663135245
#Sta/Elev= 30
9463.459  286.389474.415284.02029486.007279.49259498.486273.2367 9507.57270.5802
9523.444268.86539560.598267.46459575.653268.09639593.172267.06159610.692 267.406
9629.061265.64749657.006 265.8659665.869264.8296 9703.79263.22549783.914265.0552
9840.161260.25539873.108261.6069 9883.85260.57829894.593257.95369905.336 257.834
9915.972 255.2359926.423255.74699936.873257.339510009.14251.065610029.59255.8989
10039.87260.7324 10050.2268.366710060.53 271.68210112.69275.535610165.66275.5753
#Mann= 3 , 0 , 0
9463.459    0.12       09463.459    0.12       010165.66    0.12       0
#XS Ineff= 2 , 0
       0                               0
Bank Sta=9463.459,10165.66
Exp/Cntr=0.3,0.1